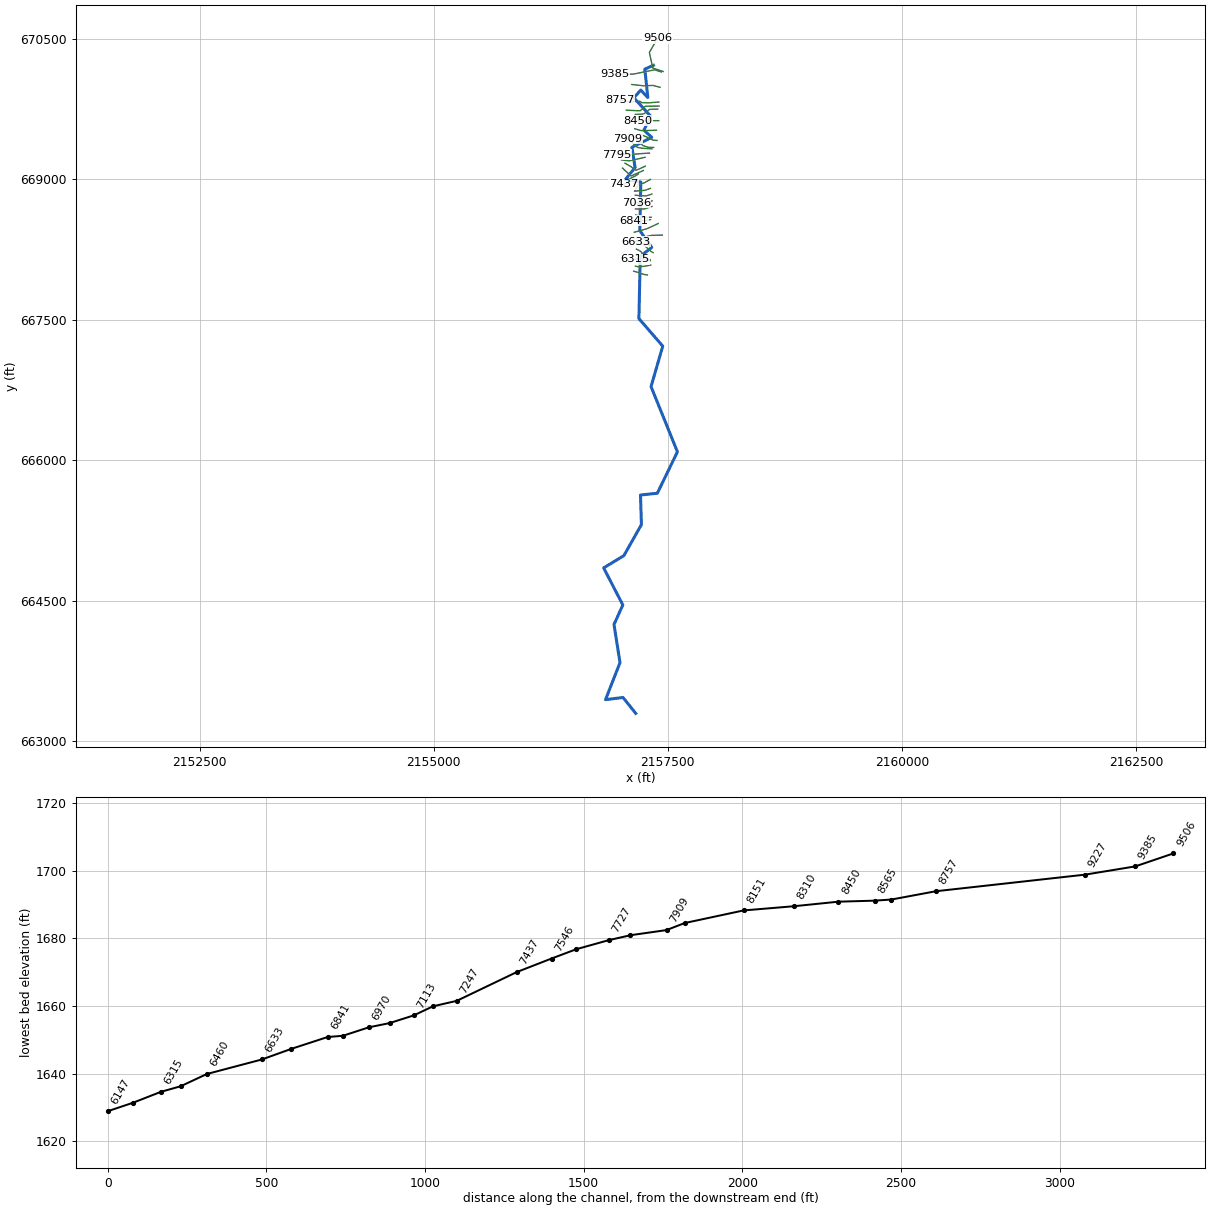
--- FLATWDSRN.prj (project) ---

Proj Title=FLATWDSRN
Current Plan=p01
Default Exp/Contr=0,0
English Units
Geom File=g01
Flow File=f01
Plan File=p01
BEGIN DESCRIPTION:
---------- MODELED AS PART OF WVEMD CTP PROGRAM, 2023----------
Stream Name: Flatwoods Run
Flood Zone:  AFH
Upshur County, WV
HEC-RAS Version: RAS 6.3
Vertical Datum: NAVD88
Projection: NAD 1983 StatePlane West Virginia S FIPS 4702 (US Feet)
Terrain: 1-meter LIDAR (FEMA Region III 3DEP collected 2016-2018)
Land Use: 2019 NLCD
Hydrologic Method:
WV SIR2010-5033 regression equations
Additional Model Notes:
None
END DESCRIPTION:
DSS Export Rating Curves= 0
DSS Export Rating Curve Sorted= 0
DSS Export Volume Flow Curves= 0
DXF OffsetX= 0
DXF OffsetY= 0
DXF ScaleX= 0
DXF ScaleY= 0

--- FLATWDSRN.p01 (plan) ---

Plan Title=Floodplain
Program Version=6.30
Short Identifier=Floodplain
Geom File=g01
Flow File=f01
Subcritical Flow
K Sum by GR= 0
Std Step Tol= 0.01
Critical Tol= 0.01
Num of Std Step Trials= 20
Max Error Tol= 0.3
Flow Tol Ratio= 0.001
Split Flow NTrial= 30
Split Flow Tol= 0.02
Split Flow Ratio= 0.02
Log Output Level= 0
Friction Slope Method= 1
Unsteady Friction Slope Method= 2
Unsteady Bridges Friction Slope Method= 1
Parabolic Critical Depth
Global Vel Dist= 0 , 0 , 0
Global Log Level= 0
CheckData=False
Encroach Param=-1 ,0,0, 0
Mapping Interval=1HOUR
Computation Time Step Use Courant=        0
Computation Time Step Use Time Series=    0
Computation Time Step Count To Double=0
Computation Time Step Max Doubling=0
Computation Time Step Max Halving=0
Computation Time Step Residence Courant=0
Run HTab= 0
Run UNet= 0
Run Sediment= 0
Run PostProcess= 0
Run WQNet= 0
Run RASMapper=-1
UNET Theta= 0
UNET Theta Warmup= 0
UNET ZTol= 0
UNET ZSATol= 0
UNET MxIter= 0
UNET Max Iter WO Improvement= 0
UNET MaxInSteps= 0
UNET DtIC= 0
UNET DtMin= 0
UNET MaxCRTS= 0
UNET WFStab= 0
UNET SFStab= 0
UNET WFX= 1
UNET SFX= 1
UNET Gravity=32.17405
UNET 1D Methodology=Finite Difference
UNET DSS MLevel= 1
UNET Pardiso=0
UNET DZMax Abort= 0
UNET Use Existing IB Tables= 0
UNET Froude Reduction=False
UNET Froude Limit= 0
UNET Froude Power= 0
UNET D1 Cores= 0
UNET WindReference=Eulerian
UNET WindDragFormulation=Hsu (1988)
UNET D2 Coriolis=0
UNET D2 Cores= 0
UNET D2 Theta= 1
UNET D2 Theta Warmup= 1
UNET D2 Z Tol= 0.01
UNET D2 Volume Tol= 0.01
UNET D2 Max Iterations= 20
UNET D2 Equation= 0
UNET D2 RampUpFraction=0.1
UNET D2 TimeSlices= 1
UNET D2 Turbulence Formulation=Non-Conservative (original)
UNET D2 Eddy Viscosity=0.3
UNET D2 Transverse Eddy Viscosity=0.1
UNET D2 Smagorinsky Mixing=0
UNET D2 BCVolumeCheck=0
UNET D2 Cores=0
UNET D2 SolverType=PARDISO (Direct)
UNET D2 Minimum Iterations= 3
UNET D2 Maximum Iterations= 30
UNET D2 Restart Number= 10
UNET D2 Relaxation Coeff=1.3
UNET D2 SOR Precondition Iterations= 10
UNET D2 ILUT Maximum Fill= 8
UNET D2 ILUT Tolerance=1E-08
UNET D2 Convergence Tolerance=0.00001
UNET D1D2 MaxIter= 0
UNET D1D2 ZTol=0.01
UNET D1D2 QTol=0.1
UNET D1D2 MinQTol=1
Write IC File= 0
Write IC File at Fixed DateTime=0
Write IC File at Sim End=0
Echo Input=False
Echo Parameters=False
Echo Output=False
Write Detailed= 0
HDF Write Warmup=0
HDF Write Time Slices=0
HDF Flush=0
HDF Compression= 1
HDF Chunk Size= 1
HDF Spatial Parts= 1
HDF Use Max Rows=0
HDF Fixed Rows= 1
Calibration Method= 0
Calibration Iterations= 20
Calibration Max Change=0.05
Calibration Tolerance=0.2
Calibration Maximum=1.5
Calibration Minimum=0.5
Calibration Optimization Method= 1
WQ AD Non Conservative
WQ ULTIMATE=-1
WQ Max Comp Step=1HOUR
WQ Output Interval=15MIN
WQ Output Selected Increments= 0
WQ Output face flow=0
WQ Output face velocity=0
WQ Output face area=0
WQ Output face dispersion=0
WQ Output cell volume=0
WQ Output cell surface area=0
WQ Output cell continuity=0
WQ Output cumulative cell continuity=0
WQ Output face conc=0
WQ Output face dconc_dx=0
WQ Output face courant=0
WQ Output face peclet=0
WQ Output face adv mass=0
WQ Output face disp mass=0
WQ Output cell mass=0
WQ Output cell source sink temp=0
WQ Output nsm pathways=0
WQ Output nsm derived pathways=0
WQ Create Restart=0
WQ Fixed Restart=0
WQ System Summary=0
WQ Write To DSS=0
Sorting and Armoring Iterations= 10
XS Update Threshold= 0.02
Bed Roughness Predictor= 0
Hydraulics Update Threshold= 0.02
Energy Slope Method= 1
Volume Change Method= 1
Sediment Retention Method= 0
Sediment TS Multiplier= 1
Warm Up Method= 0
XS Weighting Method= 0
Number of US Weighted Cross Sections= 1
Number of DS Weighted Cross Sections= 1
Upstream XS Weight=0
Main XS Weight=1
Downstream XS Weight=0
Number of DS XS's Weighted with US Boundary= 1
Upstream Boundary Weight= 1
Weight of XSs Associated with US Boundary= 0
Number of US XS's Weighted with DS Boundary= 1
Downstream Boundary Weight= 0.5
Weight of XSs Associated with DS Boundary= 0.5
Percentile Method= 0
Sediment Output Level= 3
Mass or Volume Output= 0
Output Increment Type= 1
Profile and TS Output Increment= 1
Transport Output Increment 1
XS Output Flag= 0
XS Output Increment= 10
Read HDF5 Sediment Hotstart= 0
Sediment Hotstart Type= 0
Write Gradation File= 0
Read Gradation Hotstart= 0
Write HDF5 File= 1
Write Binary Output= 1
Write DSS Sediment File= 0
DSS Sediment Output Type= 1
SV Curve= 0
Specific Gage Flag= 0
Subcell Erosion Methods= 0
Subcell Deposition Methods= 0
Advection Scheme= 1
Matrix Solver= 0
Implicit Weighting Factor= 1
Maximum Outer Loop Convergence Iterations= 5
Convergence Maximum Absolute= 0.001
Convergence RMSE= 0.0001
Grain Fractions Max Abs Error= 0.001
Max Subgrid Regions= 1
Max Subgrid Length Scale= 3.402823E+38
Initial Layer Thickness= 3.402823E+38
Min Layer Thickness= 3.402823E+38
Max Layer Thickness= 3.402823E+38
Number of Layers= 5

--- FLATWDSRN.f01 (steady flow) ---

Flow Title=Flows
Program Version=6.30
Number of Profiles= 1
Profile Names=01pct
River Rch & RM=FLATWDSRN,Main,9506
     686
River Rch & RM=FLATWDSRN,Main,6460
     765
River Rch & RM=FLATWDSRN,Main,3530
     859
Boundary for River Rch & Prof#=FLATWDSRN,Main            , 1
Up Type= 0
Dn Type= 3
Dn Slope=0.02
DSS Import GetInterval= 0
DSS Import GetPeak= 0
DSS Import FillOption= 0

--- FLATWDSRN.g01 (geometry) ---

Geom Title=Geometry
Program Version=6.31

River Reach=FLATWDSRN       ,Main
Reach XY= 30
2157346.72903454670218.418867012     2157254.721       670177.14
       2157286.8       669874.35     2157210.881       669953.56
     2157137.537      669871.403     2157317.906      669674.694
     2157245.249      669525.774     2157328.695      669449.168
     2157116.934      669342.142     2157150.644      669126.432
     2157048.197      668999.747     2157211.854      668971.761
2157201.89252298668453.063504162     2157328.838      668273.463
     2157206.045      668177.656     2157191.622       667513.87
     2157446.394       667219.35      2157321.14      666787.443
     2157602.983      666090.691     2157388.532      665648.511
     2157208.563      665629.767     2157218.522      665313.413
      2157030.77      664981.778     2156815.145      664851.573
     2157019.838      664455.436      2156925.49      664246.851
     2156989.762      663839.898     2156835.091      663444.648
      2157021.67       663467.77     2157157.512      663297.875

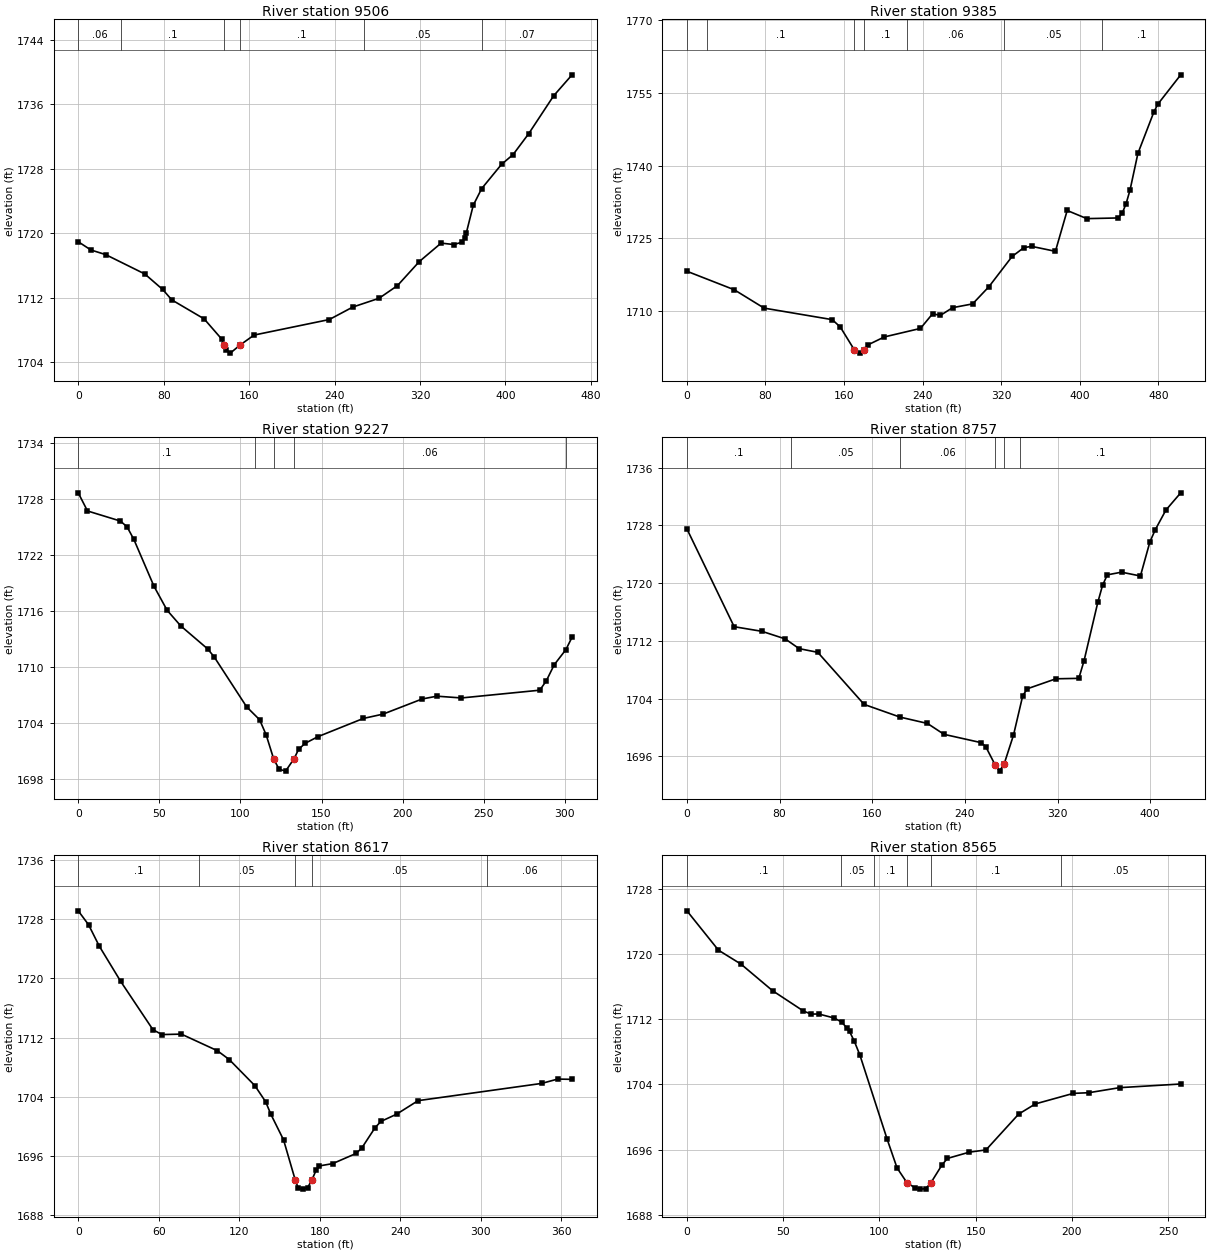
Type RM Length L Ch R = 1 ,9506    ,120.4,120.4,120.4
XS GIS Cut Line= 4
2157451.33539363670151.8848857362157339.96432213670188.586716116
2157303.26249175670355.6433233652157390.58753645 670506.24738596
#Sta/Elev= 30
       0 1718.95    11.8 1717.93    25.7 1717.35    62.3 1714.95    79.1 1713.02
    87.6 1711.73   117.9 1709.37   134.3 1706.87  136.71 1706.07   138.3 1705.57
   142.4 1705.12   151.2 1706.09   164.6 1707.36   235.1 1709.29   257.1 1710.84
   281.7 1711.93   298.9  1713.5   319.4 1716.49   339.8 1718.78   351.6  1718.6
   359.4 1718.89   361.9 1719.39   363.3 1719.99   369.9 1723.48   377.8 1725.55
   396.4 1728.56   407.2 1729.77   421.8 1732.36   445.2 1737.07   462.4 1739.67
#Mann= 6 ,-1,0
       0     .06       0      40      .1       0  136.71    .045       0
   151.2      .1       0  267.26     .05       0   378.3     .07       0
Bank Sta=136.71,151.2
XS Rating Curve= 0 ,0
Exp/Cntr(USF)=0,0
Exp/Cntr=0.3,0.1

Type RM Length L Ch R = 1 ,9385    ,158.3,158.3,158.3
XS GIS Cut Line= 4
2157430.76071866670146.6292251132157360.62902974670170.542819073
 2157136.2431728670124.9161001962156936.60164597670120.417326684
#Sta/Elev= 30
       0 1718.18    48.2 1714.36    78.6 1710.57     148 1708.19   156.2 1706.66
   170.3 1702.01   176.6 1701.28   180.8 1701.99   184.8 1703.03     201 1704.62
   237.8 1706.38   250.1 1709.39   258.2 1709.08   270.5 1710.66   290.9 1711.44
   307.5 1714.99   331.1 1721.23   343.2 1723.07   351.2 1723.31   375.2 1722.29
   387.2 1730.72   407.2 1729.04   439.2 1729.18   443.2 1730.15   447.2 1732.14
   451.2 1734.96   459.2  1742.5   475.3 1750.97   479.4 1752.64   502.8 1758.72
#Mann= 7 ,-1,0
       0     .06       0      20      .1       0   170.3    .045       0
   180.8      .1       0   224.1     .06       0  323.07     .05       0
  423.07      .1       0
Bank Sta=170.3,180.8
XS Rating Curve= 0 ,0
Exp/Cntr(USF)=0,0
Exp/Cntr=0.3,0.1

Type RM Length L Ch R = 1 ,9227    ,469,470,461.7
XS GIS Cut Line= 4
2157417.31439122669983.3361302742157340.71626421670003.452810097
2157239.35914664669999.5842178232157116.33791235670013.511150008
#Sta/Elev= 30
       0 1728.62     5.7 1726.68      26  1725.6    30.1 1724.98    34.3 1723.63
    46.7 1718.62    54.8 1716.05    63.2 1714.38    79.7 1711.93    83.7 1711.09
   103.8 1705.72   111.8 1704.34   115.8 1702.74   120.5 1700.13   123.8 1699.05
   127.8 1698.84   133.11700.181   135.8 1701.16   139.8 1701.81   147.8 1702.53
   175.8 1704.48   187.9 1704.94     212 1706.56   221.1 1706.86   236.2 1706.67
   284.5  1707.5   288.5 1708.49   293.4 1710.22   300.6 1711.84   304.4 1713.17
#Mann= 5 ,-1,0
       0      .1       0   109.2     .06       0   120.5    .045       0
   133.1     .06       0  300.63      .1       0
Bank Sta=120.5,133.1
XS Rating Curve= 0 ,0
Exp/Cntr(USF)=0,0
Exp/Cntr=0.3,0.1

Type RM Length L Ch R = 1 ,8757    ,133.9,139.8,143.7
XS GIS Cut Line= 6
2157404.85150629669825.9420237842157287.65637196669817.168056507
2157221.22490544669819.6749043012157202.42354699669834.089279112
 2157088.3619724669828.4488715772156986.20792483669850.383789768
#Sta/Elev= 30
       0 1727.52    40.8 1713.96    64.8 1713.32    84.9 1712.27    96.9 1710.92
     113 1710.41     153 1703.19     184 1701.43   207.7 1700.55     222 1699.04
     254 1697.89     258 1697.34     266 1694.85     270 1693.94     274 1694.97
     282 1698.93     290 1704.41     294 1705.36   318.6 1706.74   338.4  1706.8
   342.9 1709.23   354.8 1717.34   358.9  1719.7     363 1721.15   375.3 1721.52
   391.6 1720.99   399.8 1725.73   404.5 1727.43   413.6 1730.13   426.4 1732.52
#Mann= 6 ,-1,0
       0      .1       0      90     .05       0     184     .06       0
     266    .045       0     274     .06       0  287.69      .1       0
Bank Sta=266,274
XS Rating Curve= 0 ,0
Exp/Cntr(USF)=0,0
Exp/Cntr=0.3,0.1

Type RM Length L Ch R = 1 ,8617    ,53.1,52.7,52.3
XS GIS Cut Line= 5
2157407.86299046669783.0430607822157262.46581845669781.789636885
2157205.43503115669733.532816866  2157170.965874669733.532816866
2157057.53101135  669739.1732244
#Sta/Elev= 30
       0 1729.14     7.7 1727.26    15.7 1724.36    31.7 1719.58    55.7 1713.06
    62.4  1712.4    76.9 1712.46   103.7 1710.22   112.6 1709.02   131.7 1705.49
   139.7 1703.32   143.7 1701.59   153.1 1698.15   161.7 1692.79   164.1  1691.6
   167.3 1691.49   171.1 1691.71   174.31692.764   177.3 1694.02   179.8 1694.63
   189.7 1694.94   207.1 1696.31   211.3 1697.02   221.4 1699.82   225.7 1700.65
   237.4 1701.63   253.4 1703.46   345.5 1705.79   357.5 1706.38   368.2 1706.34
#Mann= 5 ,-1,0
       0      .1       0      90     .05       0   161.7    .045       0
   174.3     .05       0  304.58     .06       0
Bank Sta=161.7,174.3
XS Rating Curve= 0 ,0
Exp/Cntr(USF)=0,0
Exp/Cntr=0.3,0.1

Type RM Length L Ch R = 1 ,8565    ,121.1,114.8,108
XS GIS Cut Line= 5
2157392.61299971 669750.454039472157305.56967356669747.668653033
2157247.77290499669702.4061234332157224.79346689669696.835350559
2157152.37341953669694.049964122
#Sta/Elev= 30
       0 1725.31    16.4 1720.48    28.1 1718.77    44.5 1715.51    60.5 1713.02
    64.5 1712.64    68.5 1712.65    76.5 1712.16    80.5 1711.65    83.1 1710.93
    84.5 1710.51      87  1709.3    89.9  1707.6   104.1 1697.25   109.2 1693.76
   114.3 1691.96   118.3 1691.35   121.2 1691.16     124 1691.21   126.61691.871
   132.6 1694.15   135.4 1694.93   146.8  1695.7   155.4 1695.97   172.4 1700.37
   181.1 1701.62   200.8 1702.91   208.8 1702.99   224.8 1703.61   256.6 1704.06
#Mann= 6 ,-1,0
       0      .1       0      80     .05       0   97.09      .1       0
   114.3    .045       0   126.6      .1       0  194.14     .05       0
Bank Sta=114.3,126.6
XS Rating Curve= 0 ,0
Exp/Cntr(USF)=0,0
Exp/Cntr=0.3,0.1

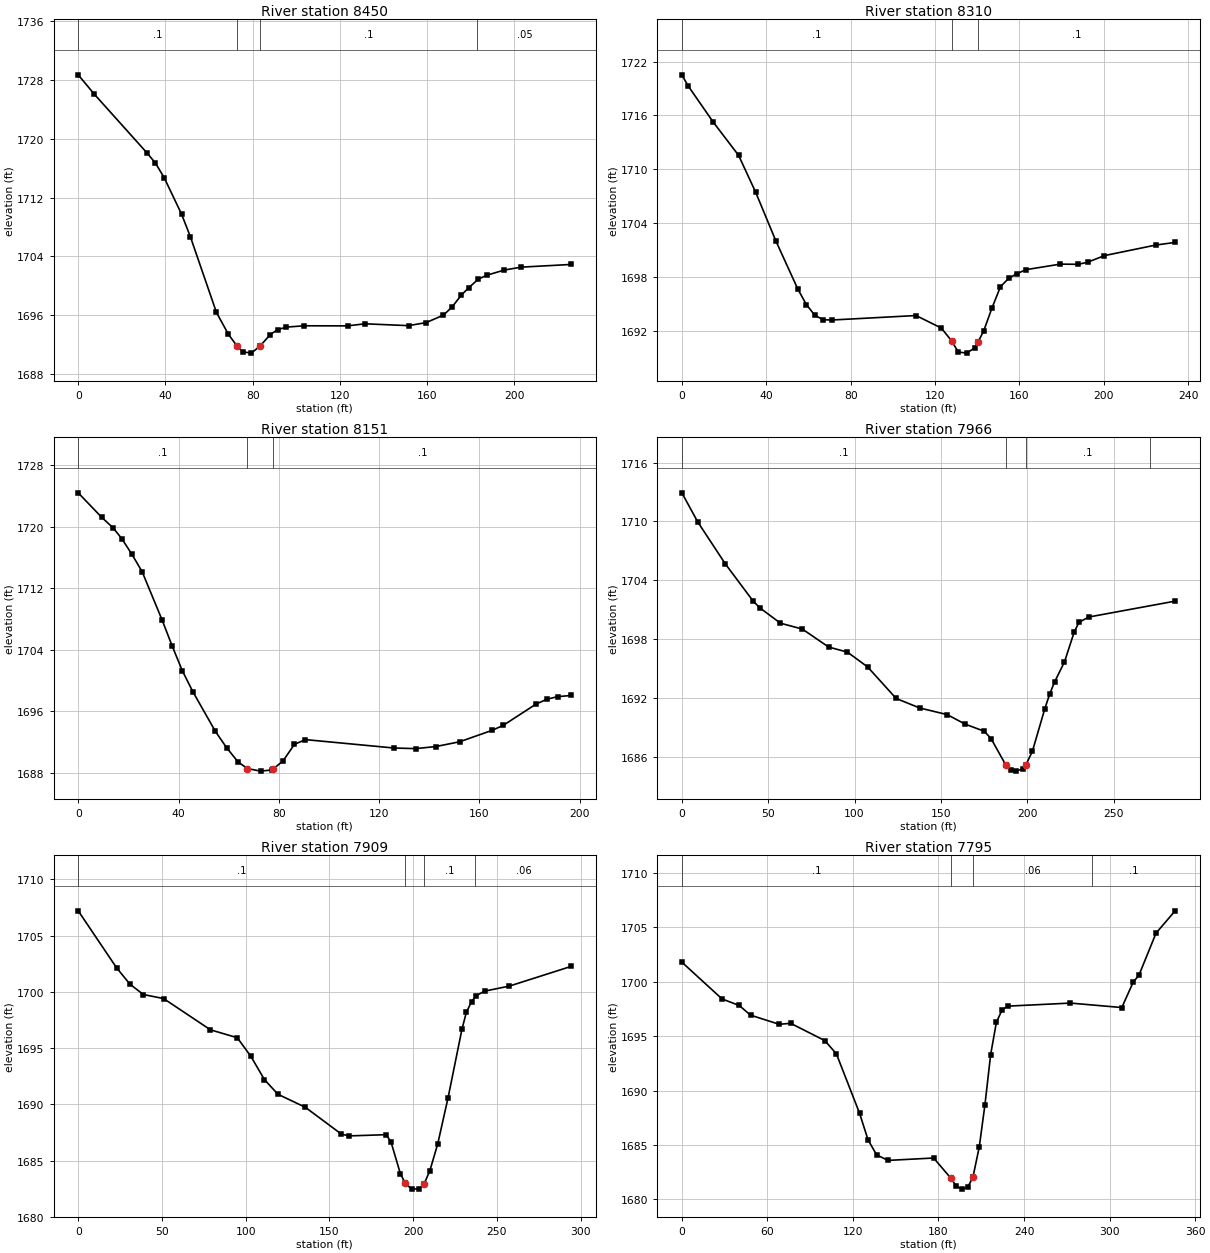
Type RM Length L Ch R = 1 ,8450    ,139.5,139.9,139.8
XS GIS Cut Line= 5
2157403.58463689669627.0572422352157350.35659843669627.376168982
2157304.95828124669625.4041153842157220.67179131669624.870017535
2157177.48715999669626.379696984
#Sta/Elev= 30
       0 1728.72     7.4 1726.08    31.4 1718.14    35.4 1716.72    39.4 1714.74
    47.4 1709.76    51.4 1706.72    63.4 1696.38    68.9  1693.4    72.8 1691.83
    75.4 1691.03    79.4 1690.85    83.4 1691.82    88.1 1693.38    91.4 1694.04
    95.5 1694.39   103.6 1694.57   123.5 1694.56   131.5 1694.84   151.5 1694.59
   159.5    1695   167.5 1696.02   171.5 1697.15   175.7 1698.75   179.2 1699.78
   183.5 1700.92   187.3 1701.44   195.3 1702.15   203.1 1702.55   226.2 1702.92
#Mann= 4 ,-1,0
       0      .1       0    72.8    .045       0    83.4      .1       0
  182.96     .05       0
Bank Sta=72.8,83.4
XS Rating Curve= 0 ,0
Exp/Cntr(USF)=0,0
Exp/Cntr=0.3,0.1

Type RM Length L Ch R = 1 ,8310    ,160,158.9,151.3
XS GIS Cut Line= 4
2157379.08835249669525.6901409272157323.99626225669522.993390202
2157213.82733978669521.4402119232157148.02258521669540.241570372
#Sta/Elev= 30
       0 1720.53     2.9 1719.32    14.9 1715.25    26.9 1711.55      35 1707.43
    44.6 1701.99      55 1696.63      59 1694.93      63 1693.73      67 1693.23
      71  1693.2     111  1693.7     123  1692.3   127.8 1690.89     131 1689.64
     135 1689.51     139 1690.13   140.31690.726     143 1691.95     147 1694.55
     151 1696.91     155 1697.87     159 1698.38     163 1698.81   179.4 1699.43
   187.9 1699.41   192.3 1699.64   200.3 1700.38   224.7 1701.56   233.8 1701.85
#Mann= 3 ,-1,0
       0      .1       0   127.8    .045       0   140.3      .1       0
Bank Sta=127.8,140.3
XS Rating Curve= 0 ,0
Exp/Cntr(USF)=0,0
Exp/Cntr=0.3,0.1

Type RM Length L Ch R = 1 ,8151    ,186.1,185.4,179.5
XS GIS Cut Line= 4
2157385.54641362669415.5258926592157341.67657723669419.286164349
2157286.52592578669447.4882020232157203.17323666669483.210783076
#Sta/Elev= 30
       0 1724.38     9.4 1721.19    13.9 1719.84    17.4 1718.42    21.4 1716.41
    25.5 1714.14    33.5 1707.84    37.5 1704.48    41.5  1701.3    45.7 1698.58
    54.7 1693.42    59.2 1691.29    63.7 1689.47    67.4  1688.6    72.7 1688.26
    77.2 1688.41    77.8 1688.55    81.7 1689.59    86.2 1691.73    90.6 1692.35
   125.9 1691.26   134.6 1691.18   142.6 1691.45   152.1 1692.07   165.1 1693.56
   169.5  1694.2   182.5 1696.95   186.9 1697.59   191.2 1697.93   196.7 1698.08
#Mann= 3 ,-1,0
       0      .1       0    67.4    .045       0    77.8      .1       0
Bank Sta=67.4,77.8
XS Rating Curve= 0 ,0
Exp/Cntr(USF)=0,0
Exp/Cntr=0.3,0.1

Type RM Length L Ch R = 1 ,7966    ,56.6,57.2,57.8
XS GIS Cut Line= 6
2157349.36488131669340.9393513832157292.25575502669342.309970414
2157234.68975572669360.5848908262157210.01861316669384.342287363
2157147.88388376669448.7613818172157108.21754368669468.826330823
#Sta/Elev= 30
       0 1712.91     9.2 1709.94    25.2 1705.66    41.2 1701.89    45.2 1701.18
    57.1 1699.62    69.8 1699.02      85 1697.19    95.9 1696.67   107.6 1695.16
   124.1 1691.95   137.7 1690.98   153.7  1690.3   164.1 1689.33   175.2  1688.6
   179.1 1687.85   187.6 1685.17   190.4 1684.68   193.3 1684.54   197.4 1684.76
   199.21685.161     203 1686.55   210.2 1690.89   213.1 1692.43   215.9 1693.64
   221.6 1695.67   227.2  1698.7     230 1699.71   235.7 1700.25   285.7 1701.87
#Mann= 4 ,-1,0
       0      .1       0   187.6    .045       0   199.2      .1       0
  271.27     .06       0
Bank Sta=187.6,199.2
XS Rating Curve= 0 ,0
Exp/Cntr(USF)=0,0
Exp/Cntr=0.3,0.1

Type RM Length L Ch R = 1 ,7909    ,104.3,113.7,122.2
XS GIS Cut Line= 4
2157331.04845863669326.0752759322157227.29281386669332.342395414
2157175.06681817669342.0912479442157074.09655983 669435.40169358
#Sta/Elev= 30
       0  1707.2    22.9 1702.14    30.9 1700.68    38.9 1699.76      51  1699.4
      79 1696.62      95 1695.92   103.1 1694.27   111.2  1692.2   119.3 1690.89
   135.6 1689.74   157.1 1687.36   161.6 1687.19   183.9  1687.3   186.8 1686.66
   192.4 1683.84   195.3 1682.99   199.1 1682.46   203.8  1682.5   206.6 1682.93
     210 1684.09   214.7 1686.47   220.9 1690.59   229.2 1696.68   231.8 1698.17
   234.9 1699.12   237.7 1699.66   242.7 1700.06   257.5 1700.51   294.6 1702.27
#Mann= 4 ,-1,0
       0      .1       0   195.3    .045       0   206.6      .1       0
  237.07     .06       0
Bank Sta=195.3,206.6
XS Rating Curve= 0 ,0
Exp/Cntr(USF)=0,0
Exp/Cntr=0.3,0.1

Type RM Length L Ch R = 1 ,7795    ,64.4,68,70.2
XS GIS Cut Line= 5
2157304.28372239669280.9789525182157199.62282702669274.085121087
2157185.20845221669271.5782732932157076.78728516669268.444713552
2156958.79522081669265.527794978
#Sta/Elev= 30
       0  1701.8    28.2 1698.42    40.2 1697.82    48.2 1696.93    68.3 1696.09
    76.3 1696.18   100.3 1694.59   108.4 1693.37   124.6 1687.93   130.6 1685.47
   136.6 1684.09   144.6 1683.58   176.6  1683.8   188.6 1681.96   192.6 1681.19
   196.6 1680.94   200.6 1681.13   204.21682.057   208.6 1684.81   212.6 1688.71
   216.6 1693.31   220.6 1696.26   224.6 1697.42   228.6 1697.76   272.6 1698.04
   308.6 1697.63   316.6 1699.97   320.6  1700.6   332.6 1704.47     346 1706.52
#Mann= 4 ,-1,0
       0      .1       0   188.6    .045       0   204.2     .06       0
  287.98      .1       0
Bank Sta=188.6,204.2
XS Rating Curve= 0 ,0
Exp/Cntr(USF)=0,0
Exp/Cntr=0.3,0.1

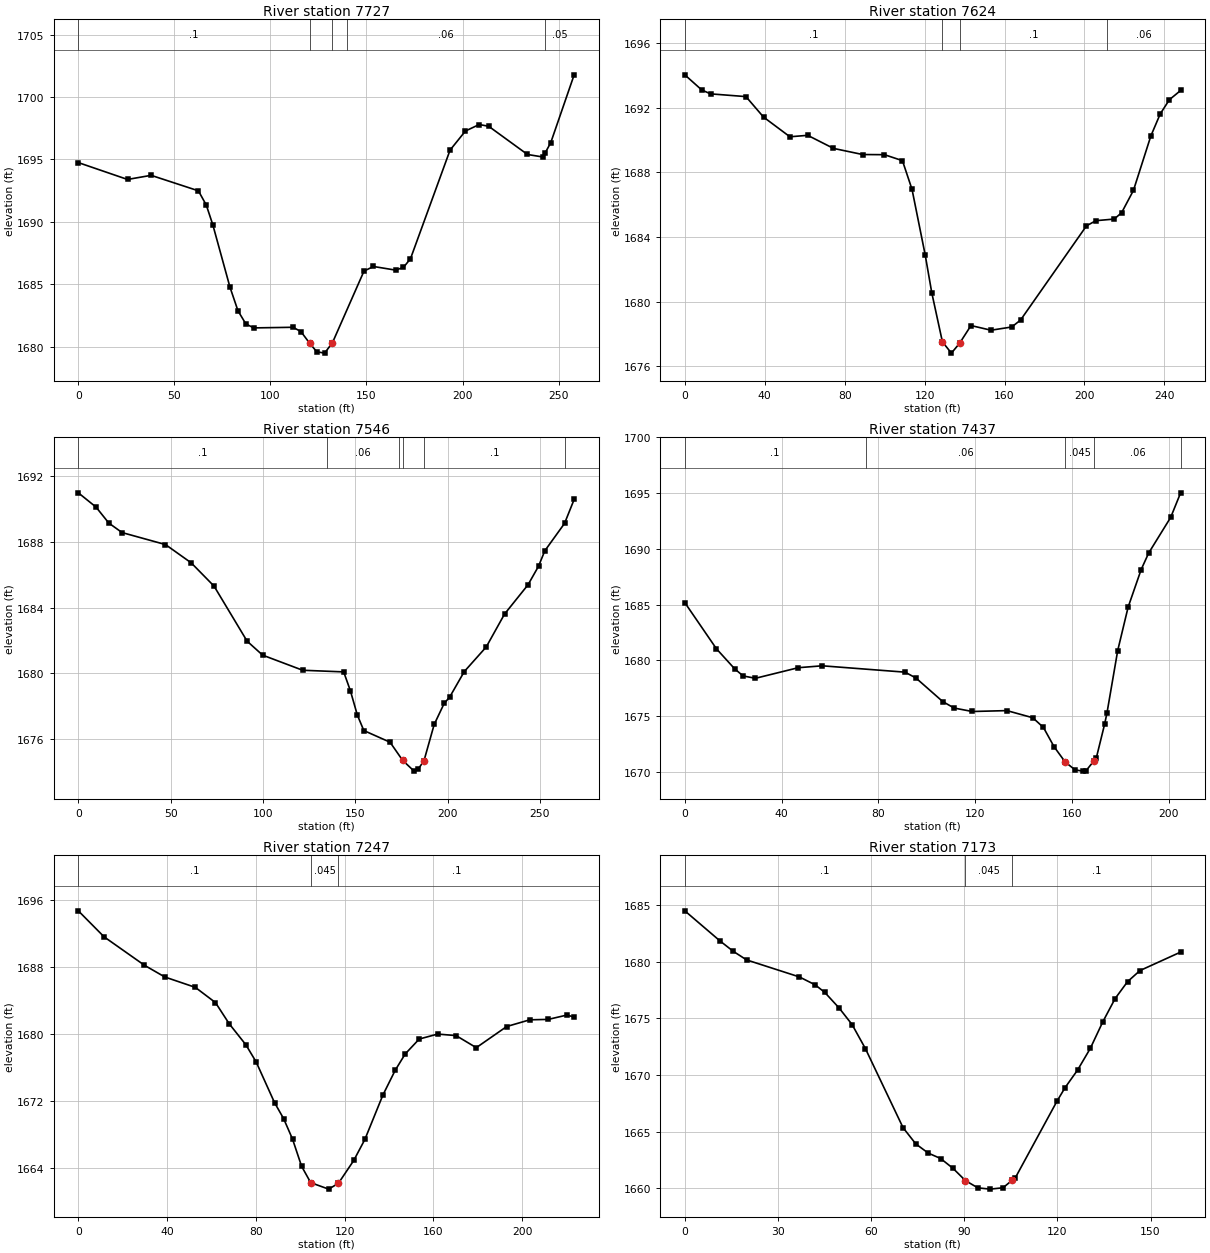
Type RM Length L Ch R = 1 ,7727    ,111,102.8,94.9
XS GIS Cut Line= 3
2157257.15508102669236.0040991772157088.56894022 669197.62676631
2157004.04743331669208.134845547
#Sta/Elev= 30
       0 1694.75    25.6  1693.4    37.9 1693.73    62.5 1692.49    66.6 1691.35
      70 1689.77    78.9 1684.79    83.1 1682.88    87.2 1681.83    91.3 1681.51
   111.8 1681.56   115.9 1681.21   120.41680.286   124.1  1679.6   128.2 1679.49
   132.3 1680.33   148.7 1686.06   153.6 1686.43   165.1 1686.14   169.2 1686.35
   172.9 1687.05   193.5 1695.75   201.5 1697.28   208.7  1697.8   213.6 1697.66
   233.8  1695.4   241.8  1695.2   242.9  1695.5   245.9 1696.34   258.1 1701.78
#Mann= 5 ,-1,0
       0      .1       0   120.4    .045       0   132.3      .1       0
     140     .06       0   242.9     .05       0
Bank Sta=120.4,132.3
XS Rating Curve= 0 ,0
Exp/Cntr(USF)=0,0
Exp/Cntr=0.3,0.1

Type RM Length L Ch R = 1 ,7624    ,78.9,77.8,77
XS GIS Cut Line= 5
2157259.89631908669141.4313860412157200.95970075669114.019005422
2157159.38425682669097.5715770512157101.36138451   669139.603894
 2157043.3385122669172.498750743
#Sta/Elev= 30
       0 1694.05     8.5 1693.11    12.9 1692.87    30.6  1692.7    39.4 1691.43
    52.6 1690.21    61.5  1690.3    74.4 1689.49      89 1689.11    99.9  1689.1
   108.9 1688.73   113.7 1686.95   120.3 1682.88   123.6 1680.53   128.9  1677.5
   133.4  1676.8   137.5 1677.41   143.2 1678.51   153.2 1678.22   163.6 1678.42
     168 1678.85     201 1684.69   205.7 1685.01   214.9 1685.11   218.6 1685.51
   224.5 1686.89   233.2 1690.26   237.9 1691.63   242.5 1692.51   248.1 1693.08
#Mann= 4 ,-1,0
       0      .1       0   128.9    .045       0   137.5      .1       0
  211.36     .06       0
Bank Sta=128.9,137.5
XS Rating Curve= 0 ,0
Exp/Cntr(USF)=0,0
Exp/Cntr=0.3,0.1

Type RM Length L Ch R = 1 ,7546    ,96,109.6,121.5
XS GIS Cut Line= 4
2157239.27967013669094.8067096272157162.00608691669060.400223665
2157108.26428391669036.0618651532157016.48357251669120.752584287
#Sta/Elev= 30
       0 1690.99     9.6 1690.12    16.5 1689.15    23.7 1688.57    47.2 1687.84
    61.1 1686.73    73.5 1685.31    91.4 1681.96    99.8 1681.11   121.5 1680.19
   143.7 1680.09   147.3 1678.95   151.1 1677.46   154.6 1676.52   168.8 1675.81
   175.6 1674.71   181.8 1674.05   184.1 1674.18   187.2 1674.69   192.7 1676.89
   198.1 1678.17   201.1 1678.56     209 1680.11   220.9 1681.61   230.8 1683.61
   243.5 1685.39   249.2 1686.52   252.6 1687.46   263.3 1689.13   268.5 1690.59
#Mann= 6 ,-1,0
       0      .1       0  134.59     .06       0  173.58      .1       0
   175.6    .045       0   187.2      .1       0  263.58     .07       0
Bank Sta=175.6,187.2
XS Rating Curve= 0 ,0
Exp/Cntr(USF)=0,0
Exp/Cntr=0.3,0.1

Type RM Length L Ch R = 1 ,7437    ,188.4,189.3,182.5
XS GIS Cut Line= 5
2157186.82388006669059.2721421582157158.62184239669038.966675033
2157097.14140026669008.5084743452157082.04976588668973.178007472
2157024.43031244668947.532354784
#Sta/Elev= 30
       0 1685.17    13.1 1681.02    20.6 1679.23    24.1 1678.59    29.2 1678.38
    46.9 1679.33    56.8  1679.5      91 1678.93    95.5 1678.41   106.6 1676.29
   111.3 1675.71   118.8  1675.4   133.1 1675.48   143.8 1674.84   148.2 1673.97
   152.6 1672.24   157.21670.866   161.3 1670.16   164.4 1670.05   165.7 1670.06
   169.2    1671   170.1 1671.27   173.5 1674.27   174.5 1675.31   178.9 1680.87
   183.2 1684.76   188.6 1688.14   191.7 1689.62   200.8 1692.82   204.9 1695.02
#Mann= 5 ,-1,0
       0      .1       0   74.75     .06       0   157.2    .045       0
   169.2     .06       0  204.85     .05       0
Bank Sta=157.2,169.2
XS Rating Curve= 0 ,0
Exp/Cntr(USF)=0,0
Exp/Cntr=0.3,0.1

Type RM Length L Ch R = 1 ,7247    ,75.9,74.8,73.6
XS GIS Cut Line= 4
2157314.29709035 668999.483822292157242.66391465668960.000969547
2157187.95196157668949.8482359842157146.52982024668874.491619936
#Sta/Elev= 30
       0 1694.71    11.6 1691.61    29.8 1688.22      39 1686.82    52.7 1685.59
    61.8 1683.77      68 1681.24    75.5 1678.74    80.1 1676.71    88.4 1671.85
    92.5 1669.94    96.5 1667.51   100.6 1664.26   104.7 1662.31   112.8 1661.54
   117.2 1662.24   124.1 1664.96   129.1 1667.46   137.2 1672.74   142.8 1675.72
   147.3 1677.66   153.6 1679.43   161.9 1680.02   170.2 1679.84   179.3  1678.4
     193 1680.92   203.4 1681.72   211.7 1681.77   220.2 1682.29   223.4 1682.04
#Mann= 3 ,-1,0
       0      .1       0   104.7    .045       0   117.2      .1       0
Bank Sta=104.7,117.2
XS Rating Curve= 0 ,0
Exp/Cntr(USF)=0,0
Exp/Cntr=0.3,0.1

Type RM Length L Ch R = 1 ,7173    ,60.8,60,58.1
XS GIS Cut Line= 4
2157314.90302784668904.1712591672157257.70225275668883.629080142
2157192.21712127668878.0450766832157159.13042151668875.405612125
#Sta/Elev= 30
       0 1684.48    11.4 1681.81    15.6 1680.91    19.9 1680.15    36.9 1678.65
      42 1677.95    45.1 1677.28    49.7 1675.91    53.9 1674.44    58.2 1672.31
    70.3 1665.35    74.4 1663.92    78.4 1663.11    82.4 1662.63    86.4 1661.76
    90.4 1660.68    94.4 1660.04    98.4 1659.93   102.5 1660.05   105.41660.706
   106.5 1660.95   119.9  1667.7   122.5 1668.89   126.5 1670.43   130.6 1672.34
   134.6 1674.67   138.6 1676.74   142.6 1678.23   146.6 1679.21   159.7 1680.84
#Mann= 3 ,-1,0
       0      .1       0    90.4    .045       0   105.4      .1       0
Bank Sta=90.4,105.4
XS Rating Curve= 0 ,0
Exp/Cntr(USF)=0,0
Exp/Cntr=0.3,0.1

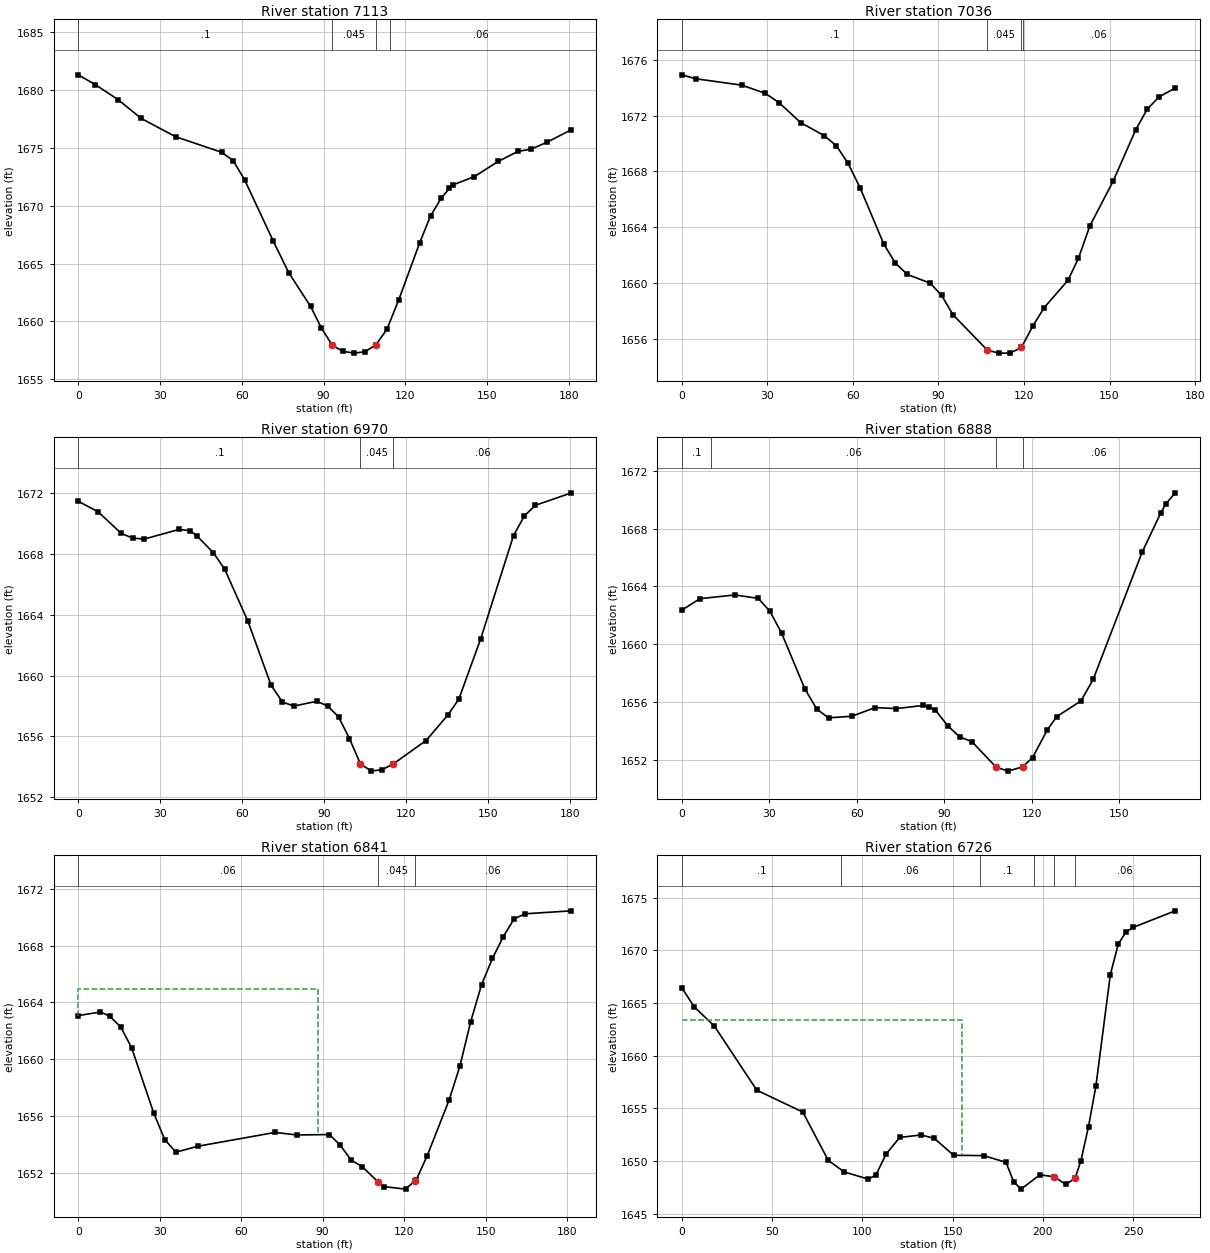
Type RM Length L Ch R = 1 ,7113    ,76.4,76.6,77.2
XS GIS Cut Line= 4
2157330.13438808668843.4289048052157268.91340469668823.326492351
2157199.92558014668826.0677304132157152.86766007668831.550206536
#Sta/Elev= 30
       0 1681.33     6.3 1680.48    14.7 1679.17    23.1 1677.56    35.7 1675.98
    52.6 1674.63    56.8 1673.92      61 1672.26    71.6 1666.92    77.2 1664.22
    85.2 1661.31    89.2 1659.43    93.2 1657.93    97.2 1657.41   101.2 1657.26
   105.2 1657.38   109.2 1657.99   113.2 1659.31   117.5 1661.84   125.2 1666.78
   129.2 1669.12   133.2 1670.69   136.1  1671.5   137.3  1671.8   145.3 1672.53
   154.1 1673.85   161.3 1674.71   166.1  1674.9   172.1 1675.52   180.9 1676.59
#Mann= 4 ,-1,0
       0      .1       0    93.2    .045       0   109.2      .1       0
  114.44     .06       0
Bank Sta=93.2,109.2
XS Rating Curve= 0 ,0
Exp/Cntr(USF)=0,0
Exp/Cntr=0.3,0.1

Type RM Length L Ch R = 1 ,7036    ,65.4,65.4,65.3
XS GIS Cut Line= 4
2157332.41875313668770.786096164 2157255.6640874 668749.76993769
2157199.01183412668748.8561916692157162.46199329668752.968048762
#Sta/Elev= 30
       0 1674.93     4.8 1674.65      21 1674.19    29.3  1673.6    34.1 1672.93
    41.7  1671.5      50 1670.56    54.2 1669.84    58.3 1668.58    62.5 1666.83
    70.8  1662.8    74.9 1661.42    79.1 1660.61    87.1 1659.99    91.1 1659.11
    95.1 1657.72   107.1 1655.19   111.1 1654.97   115.1 1654.97   119.1 1655.38
   123.1 1656.92   127.1 1658.24   135.4 1660.19   139.1 1661.78   143.1  1664.1
   151.2 1667.28   159.2    1671   163.2 1672.46   167.3 1673.34     173 1673.98
#Mann= 4 ,-1,0
       0      .1       0   107.1    .045       0   119.1      .1       0
  119.58     .06       0
Bank Sta=107.1,119.1
XS Rating Curve= 0 ,0
Exp/Cntr(USF)=0,0
Exp/Cntr=0.3,0.1

Type RM Length L Ch R = 1 ,6970    ,84.7,82.1,78.4
XS GIS Cut Line= 4
2157331.10899479668710.8414464822157251.02913473668684.380275331
2157194.62505938668683.6839287222157154.93330266668684.380275331
#Sta/Elev= 30
       0 1671.47     7.3 1670.77    15.7 1669.36    19.9 1669.04    24.2 1668.98
    36.8 1669.61      41 1669.53    43.5 1669.17    49.4 1668.09    53.6 1666.99
    62.1 1663.56    70.5 1659.38    74.7 1658.26    78.9    1658    87.2 1658.31
    91.2 1658.01    95.2 1657.29    99.2 1655.86   103.2  1654.2   107.2 1653.72
   111.2 1653.82   115.2 1654.19   127.2 1655.73   135.2 1657.41   139.2 1658.45
   147.2 1662.42   159.2 1669.21   163.2 1670.51   167.2  1671.2   180.4 1672.02
#Mann= 3 ,-1,0
       0      .1       0   103.2    .045       0   115.2     .06       0
Bank Sta=103.2,115.2
XS Rating Curve= 0 ,0
Exp/Cntr(USF)=0,0
Exp/Cntr=0.3,0.1

Type RM Length L Ch R = 1 ,6888    ,44.5,47.7,50.8
XS GIS Cut Line= 3
2157322.36881322668596.0129449642157254.11988205668592.628700443
2157157.10487245668620.266697363
#Sta/Elev= 30
       0 1662.36     6.2 1663.15    18.2 1663.41    26.2 1663.17    30.2 1662.28
    34.2 1660.77    42.2  1656.9    46.3  1655.5    50.3  1654.9    58.3 1655.01
    66.3 1655.61    73.6 1655.54    82.8 1655.76    84.9 1655.64      87 1655.43
    91.2 1654.35    95.3 1653.58    99.5 1653.25   107.8 1651.48   111.9 1651.21
   116.9 1651.51   120.3 1652.15   125.4 1654.08   128.6 1654.99   136.9 1656.07
   141.1 1657.57   157.9 1666.38   164.2 1669.06     166 1669.71   169.2 1670.48
#Mann= 4 ,-1,0
       0      .1       0      10     .06       0   107.8    .045       0
   116.9     .06       0
Bank Sta=107.8,116.9
XS Rating Curve= 0 ,0
Exp/Cntr(USF)=0,0
Exp/Cntr=0.3,0.1

Type RM Length L Ch R = 1 ,6841    ,108.4,114.6,114.5
XS GIS Cut Line= 3
2157315.60032418668571.1951518112157243.81520544668558.750881137
2157135.10728307668559.350295988
#Sta/Elev= 30
       0 1663.07     8.2 1663.32    11.6 1663.03    15.7 1662.26    19.7 1660.79
    27.8 1656.21    31.9 1654.33      36 1653.46    44.1 1653.88    72.5 1654.85
    80.5 1654.67    92.5  1654.7    96.5 1653.94   100.5  1652.9   104.5 1652.45
   110.5 1651.35   112.5 1651.04   120.5 1650.86   123.9 1651.43   124.5 1651.53
   128.5 1653.22   136.5  1657.1   140.5  1659.5   144.5 1662.64   148.5 1665.25
   152.5 1667.09   156.5 1668.62   160.5 1669.88   164.5 1670.23   181.6 1670.44
#Mann= 3 ,-1,0
       0     .06       0   110.5    .045       0   123.9     .06       0
#XS Ineff= 2 , 0
           88.23 1664.95
Permanent Ineff=
       F       F
Bank Sta=110.5,123.9
XS Rating Curve= 0 ,0
Exp/Cntr(USF)=0,0
Exp/Cntr=0.3,0.1

Type RM Length L Ch R = 1 ,6726    ,90.1,92.7,95.6
XS GIS Cut Line= 4
2157397.69226774668528.8381289162157344.89805321668503.963931687
2157274.84419163668471.9828209652157141.84338196 668435.43298014
#Sta/Elev= 30
       0 1666.44     6.9 1664.63      18 1662.82    41.5 1656.74      67 1654.66
    81.1 1650.08    89.9 1648.98   103.3  1648.3   107.5 1648.69   113.2 1650.69
   120.7 1652.25   132.5 1652.49   139.8 1652.17   150.6 1650.56   167.2 1650.53
   179.6 1649.89   183.8 1648.06   187.9 1647.35   198.4 1648.71   206.3 1648.52
   212.8 1647.79   217.9  1648.4   221.1 1650.05   225.3 1653.28   229.4 1657.13
   237.4  1667.7   241.8  1670.6     246 1671.73   250.1 1672.18   273.3 1673.75
#Mann= 6 ,-1,0
       0      .1       0   88.36     .06       0  165.37      .1       0
  195.37     .06       0   206.3    .045       0   217.9     .06       0
#XS Ineff= 2 , 0
          155.32 1663.43
Permanent Ineff=
       F       F
Bank Sta=206.3,217.9
XS Rating Curve= 0 ,0
Exp/Cntr(USF)=0,0
Exp/Cntr=0.3,0.1

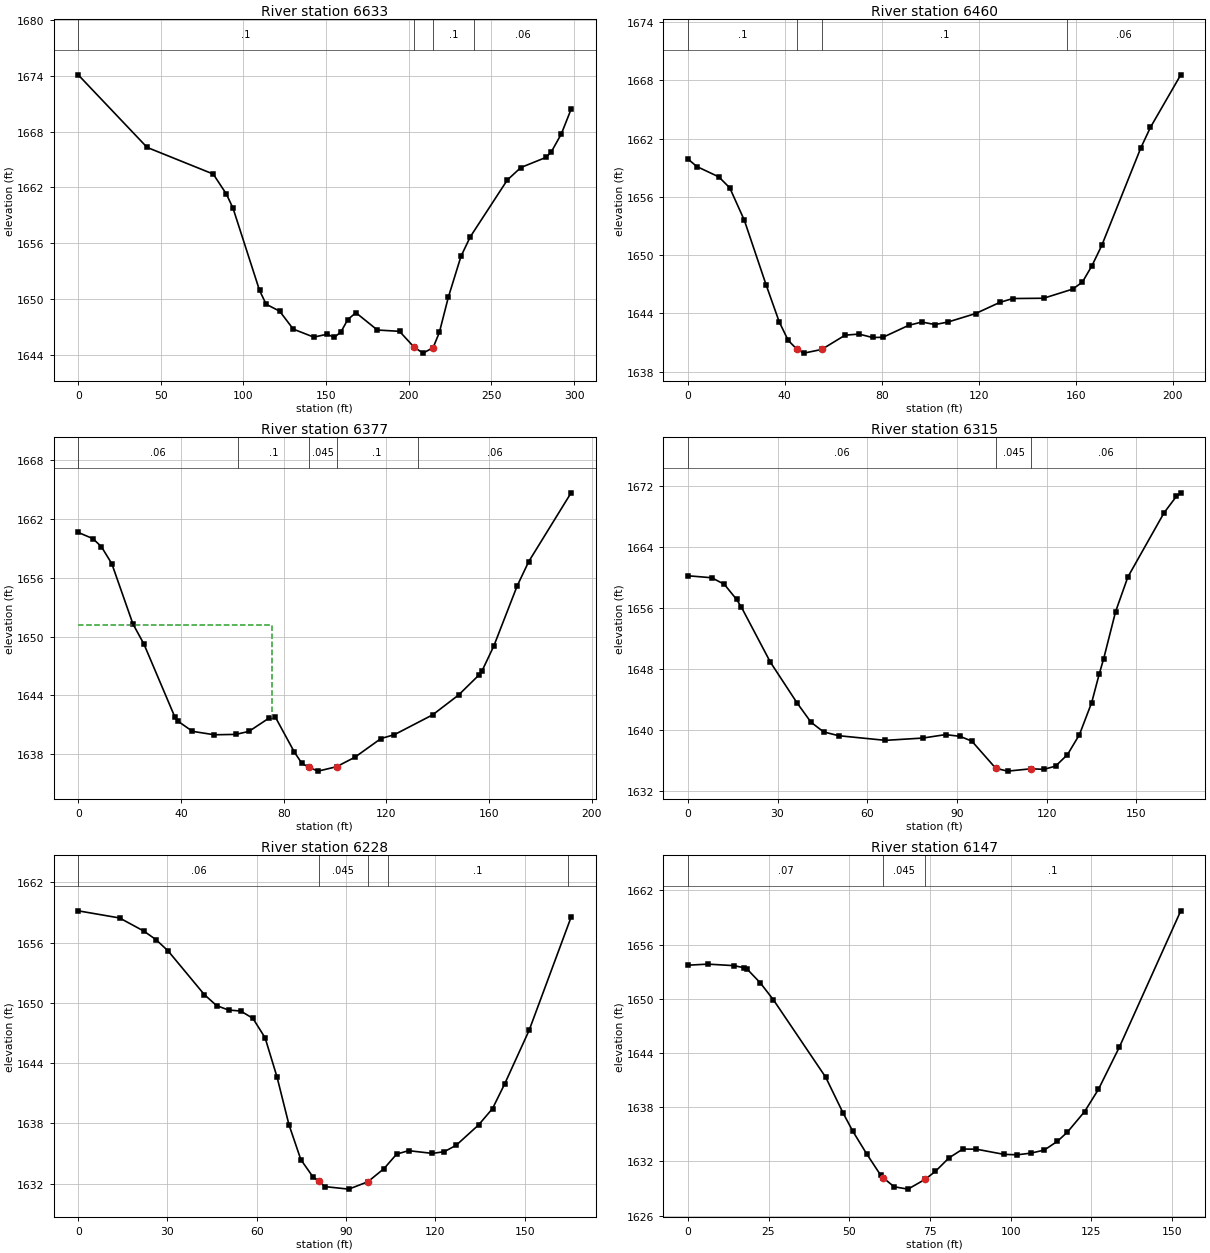
Type RM Length L Ch R = 1 ,6633    ,184.7,173.5,159.5
XS GIS Cut Line= 5
2157441.85665873 668405.482416132157324.13165198668402.256385041
2157274.05804819668389.5765815472157203.69181368668346.602376991
2157158.45994347668336.610660433
#Sta/Elev= 30
       0 1674.09    41.7  1666.3    81.7 1663.44    89.7 1661.28    93.7 1659.76
   109.7 1650.96   113.7 1649.47   121.9 1648.72   130.1  1646.8   142.5 1645.94
   150.7 1646.25   154.9  1645.9     159 1646.51   163.1 1647.82     168 1648.56
     181  1646.7   194.4 1646.56   203.1 1644.88   208.6 1644.22   214.7  1644.8
   218.5 1646.44   223.9  1650.2   231.6 1654.62   237.2  1656.7   259.6  1662.8
   267.8 1664.14   282.9 1665.22   286.2 1665.81   292.3 1667.75   298.2  1670.4
#Mann= 4 ,-1,0
       0      .1       0   203.1    .045       0   214.7      .1       0
  239.42     .06       0
Bank Sta=203.1,214.7
XS Rating Curve= 0 ,0
Exp/Cntr(USF)=0,0
Exp/Cntr=0.3,0.1

Type RM Length L Ch R = 1 ,6460    ,84,82.5,80.7
XS GIS Cut Line= 4
2157343.44333521668218.1932108322157322.88404974668229.158163079
2157238.36254283668304.5422097822157171.65908333668309.110939885
#Sta/Elev= 30
       0 1659.91     3.7 1659.13    12.8 1658.06    17.3 1656.93    23.3  1653.6
    32.3 1646.94    37.7 1643.14    41.4 1641.23    45.1  1640.3    47.9 1639.92
    55.21640.297    64.9 1641.77    70.6 1641.88    76.2 1641.53    80.5 1641.55
    91.2 1642.79    96.6 1643.12     102 1642.86   107.3 1643.12   118.7 1643.99
   128.8 1645.15   134.1 1645.54   146.8 1645.57   158.8 1646.51   162.8 1647.23
   166.8 1648.94   170.8 1651.01   186.9 1661.04   190.9 1663.17   203.4 1668.57
#Mann= 4 ,-1,0
       0      .1       0    45.1    .045       0    55.2      .1       0
  156.56     .06       0
Bank Sta=45.1,55.2
XS Rating Curve= 0 ,0
Exp/Cntr(USF)=0,0
Exp/Cntr=0.3,0.1

Type RM Length L Ch R = 1 ,6377    ,50.6,62.3,72
XS GIS Cut Line= 5
2157312.88924834668143.0753380012157275.63434575668151.872324813
2157259.83557432668169.7646717382157210.03641619668231.442528131
2157165.71973419668255.656797678
#Sta/Elev= 30
       0  1660.6     5.7 1659.97       9 1659.16    13.1 1657.41    21.3 1651.29
    25.6 1649.23    37.7 1641.77    38.8 1641.39    44.5 1640.35      53    1640
    61.4 1640.04    66.5 1640.35    74.3  1641.7    76.8 1641.78    84.2 1638.22
    87.1 1637.09    89.9 1636.68    93.4  1636.3   100.61636.751   107.7 1637.71
   117.9 1639.62   123.1 1640.01     138 1642.03   148.1 1644.05   155.9 1646.05
   157.2 1646.49   161.8 1649.03   170.9 1655.15   175.4 1657.63   191.9 1664.63
#Mann= 5 ,-1,0
       0     .06       0   62.15      .1       0    89.9    .045       0
   100.6      .1       0  132.15     .06       0
#XS Ineff= 2 , 0
           75.36 1651.14
Permanent Ineff=
       F       F
Bank Sta=89.9,100.6
XS Rating Curve= 0 ,0
Exp/Cntr(USF)=0,0
Exp/Cntr=0.3,0.1

Type RM Length L Ch R = 1 ,6315    ,87.3,87.5,87.2
XS GIS Cut Line= 4
2157311.91921372 668130.949488852157225.57021477668154.706885386
2157177.59854869668151.5087743142157150.64304108668147.396917221
#Sta/Elev= 30
       0 1660.23       8 1659.97    12.2 1659.11    16.3 1657.13    17.9 1656.13
    27.6 1648.92    36.5  1643.6    41.2 1641.05    45.4 1639.79    50.4 1639.29
    66.1 1638.68    78.6 1638.98    86.2 1639.43      91 1639.21      95 1638.58
     103 1635.02     107 1634.65   114.9 1634.96     119 1634.88     123  1635.3
     127 1636.81     131 1639.43   135.1 1643.63   137.6 1647.34   139.1 1649.36
   143.1 1655.54   147.2 1660.07   159.3 1668.47   163.4 1670.61   164.9 1671.09
#Mann= 3 ,-1,0
       0     .06       0     103    .045       0   114.9     .06       0
Bank Sta=103,114.9
XS Rating Curve= 0 ,0
Exp/Cntr(USF)=0,0
Exp/Cntr=0.3,0.1

Type RM Length L Ch R = 1 ,6228    ,85.2,80.2,74.4
XS GIS Cut Line= 4
2157317.78197407668085.1806823292157254.83502598668072.997402053
2157184.73040073668066.4488889062157154.32296371668072.997402053
#Sta/Elev= 30
       0 1659.16    13.9 1658.45      22 1657.15    26.1  1656.3    30.2 1655.17
    42.4 1650.81    46.5 1649.72    50.5 1649.28    54.6 1649.18    58.7 1648.45
    62.8 1646.51    66.8 1642.61    70.8 1637.87    74.8 1634.38    78.8 1632.69
    80.81632.202    82.9 1631.69    90.9 1631.44    97.3 1632.17   102.7 1633.47
     107 1634.93     111 1635.27     119    1635     123 1635.17     127 1635.81
   134.5 1637.83   139.2 1639.46   143.3 1641.93   151.5 1647.26   165.6 1658.53
#Mann= 5 ,-1,0
       0     .06       0    80.8    .045       0    97.3     .07       0
  104.12      .1       0  164.52     .06       0
Bank Sta=80.8,97.3
XS Rating Curve= 0 ,0
Exp/Cntr(USF)=0,0
Exp/Cntr=0.3,0.1

Type RM Length L Ch R = 1 ,6147    ,46.5,47.4,48.5
XS GIS Cut Line= 4
 2157282.2474066667979.0846165992157238.59065228667986.699166771
2157192.39571457 668003.451177152157135.54040662668020.203187528
#Sta/Elev= 30
       0 1653.71     6.2 1653.83    14.3 1653.66    17.4 1653.43    18.3  1653.3
    22.4 1651.77    26.5 1649.88    42.7 1641.31    48.1 1637.34    51.1 1635.33
    55.4 1632.82    59.7 1630.48    60.6 1630.15    63.9 1629.18    68.2 1628.92
    73.51630.004    76.7 1630.89    80.9 1632.38    85.2 1633.36    89.4 1633.34
    97.9 1632.77     102 1632.72   106.2  1632.9   110.4 1633.24   114.5 1634.22
   117.6 1635.24   122.9  1637.5   127.2 1639.97   133.7 1644.66   152.7 1659.73
#Mann= 3 ,-1,0
       0     .07       0    60.6    .045       0    73.5      .1       0
Bank Sta=60.6,73.5
XS Rating Curve= 0 ,0
Exp/Cntr(USF)=0,0
Exp/Cntr=0.3,0.1