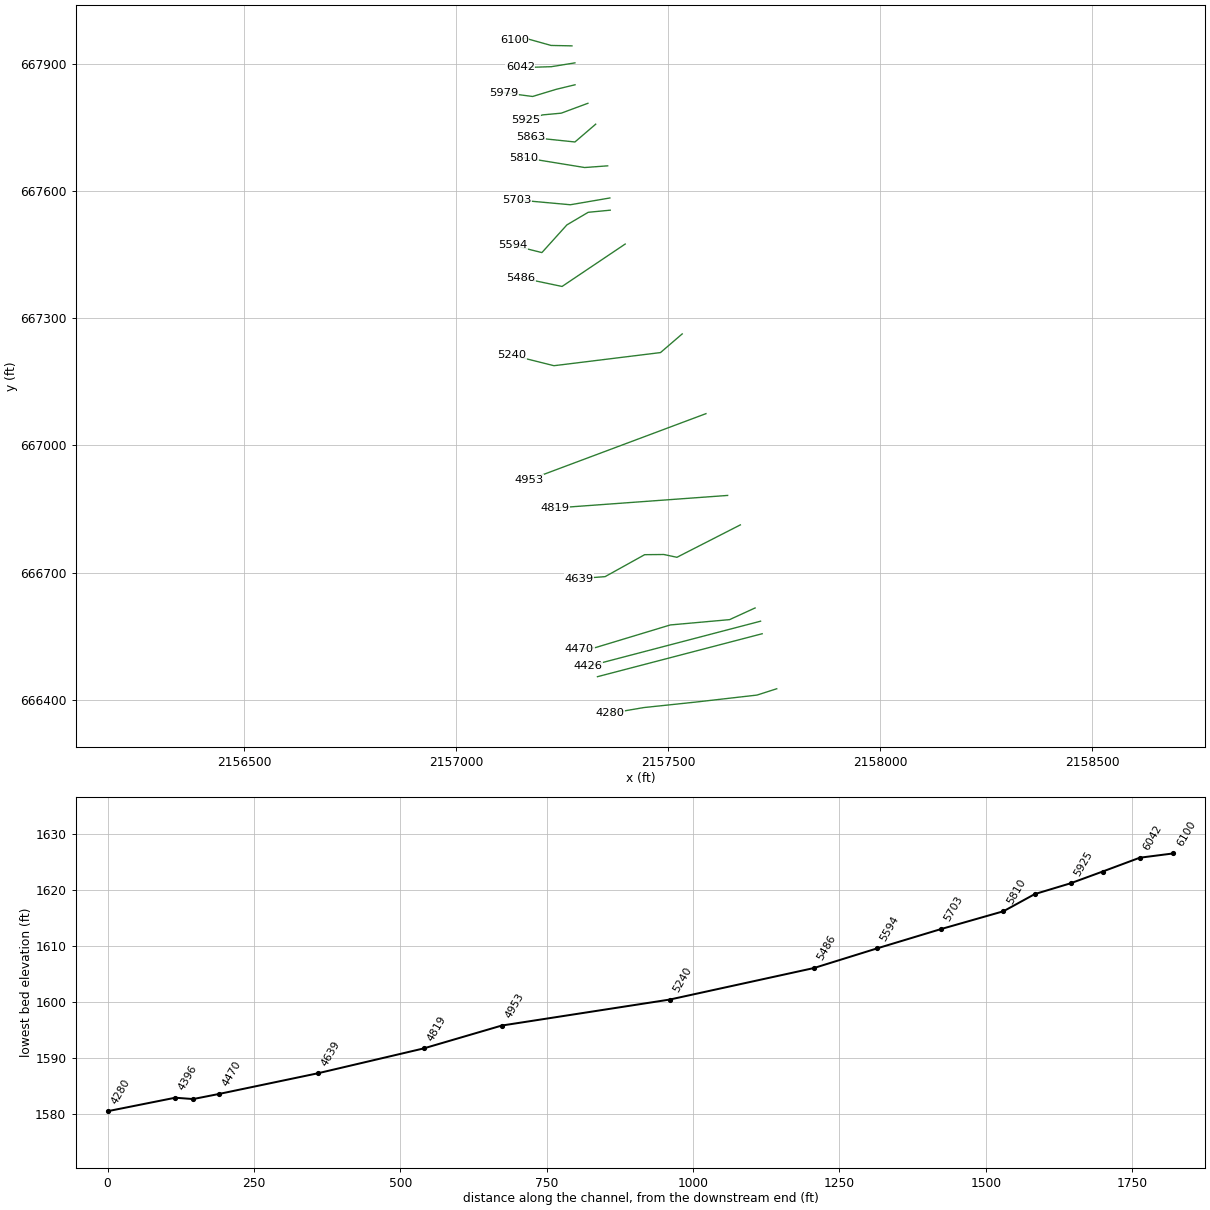
HEC-RAS study FLATWDSRN.prj: FLATWDSRN

--- FLATWDSRN.g01 (geometry) --- (continued)

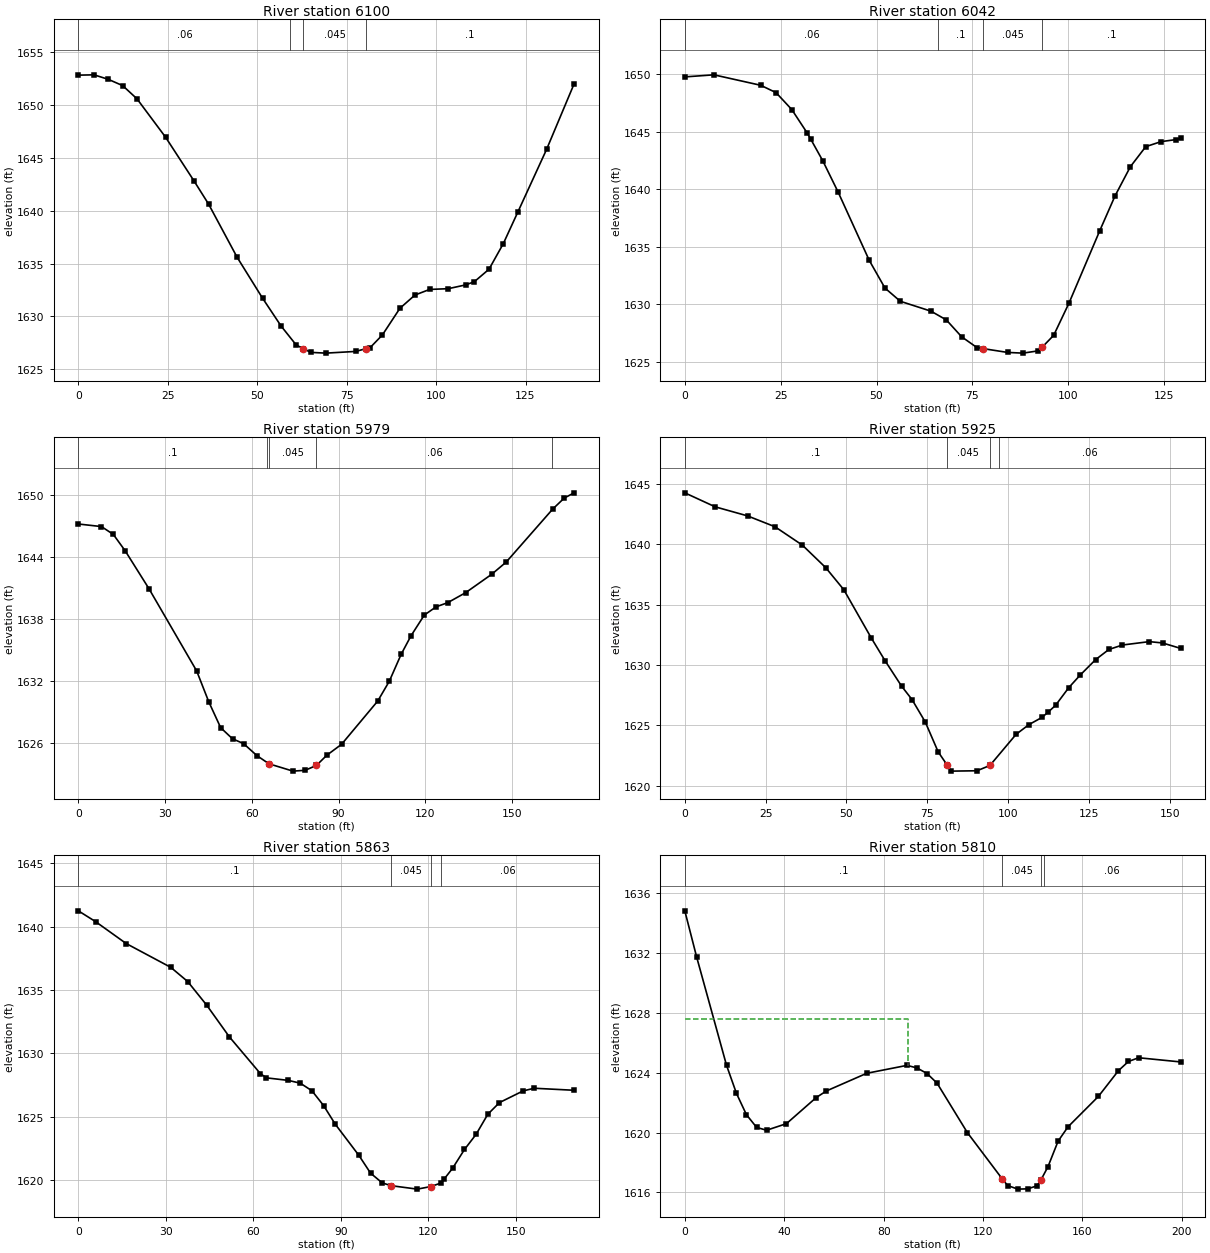
Type RM Length L Ch R = 1 ,6100    ,53.9,57.6,61.9
XS GIS Cut Line= 4
2157272.60230972667942.5347757742157223.36155194 667943.55004913
2157163.46042392667960.3020595082157136.55567998667956.748602762
#Sta/Elev= 30
       0  1652.8     4.4 1652.83     8.4  1652.4    12.4 1651.81    16.4 1650.56
    24.4 1646.93    32.4 1642.77    36.4 1640.62    44.4 1635.58    51.5 1631.72
    56.7 1629.08    60.9  1627.3    62.9 1626.95      65  1626.6    69.2 1626.53
    77.5 1626.69    80.3 1626.94    81.6 1627.06      85 1628.25    89.9 1630.77
    94.1 1632.02    98.2 1632.55   103.4 1632.62   108.3 1632.98   110.7 1633.28
   114.8 1634.46   118.8 1636.88   122.8 1639.82   130.9 1645.79   138.6 1651.99
#Mann= 4 ,-1,0
       0     .06       0   59.25      .1       0    62.9    .045       0
    80.3      .1       0
Bank Sta=62.9,80.3
XS Rating Curve= 0 ,0
Exp/Cntr(USF)=0,0
Exp/Cntr=0.3,0.1

Type RM Length L Ch R = 1 ,6042    ,60.2,63.5,66.7
XS GIS Cut Line= 4
2157279.66917694667902.4414291342157224.38114647667893.448797672
2157172.09065982667891.7834955492157151.10785308667892.116555974
#Sta/Elev= 30
       0 1649.79     7.6 1649.97    19.8 1649.06    23.8 1648.42    27.9 1646.95
    31.9 1644.92    32.8  1644.4      36 1642.48      40 1639.76    48.1 1633.83
    52.2 1631.42    56.2 1630.27    64.2 1629.41    68.2 1628.65    72.2 1627.18
    76.2 1626.24    77.81626.152    84.2 1625.82    88.2 1625.76    92.2 1625.96
    93.2 1626.28    96.2 1627.31   100.2 1630.12   108.2  1636.4   112.2 1639.44
   116.2 1641.98   120.2 1643.72   124.2 1644.16   128.2 1644.34   129.3 1644.46
#Mann= 4 ,-1,0
       0     .06       0   66.01      .1       0    77.8    .045       0
    93.2      .1       0
Bank Sta=77.8,93.2
XS Rating Curve= 0 ,0
Exp/Cntr(USF)=0,0
Exp/Cntr=0.3,0.1

Type RM Length L Ch R = 1 ,5979    ,55.9,54.4,51.1
XS GIS Cut Line= 4
 2157279.9089491667850.7496980892157236.03826133667840.196136462
 2157179.7880563667823.1730480982157112.89341464667831.916765137
#Sta/Elev= 30
       0 1647.23       8 1646.98    12.1 1646.22    16.2 1644.63    24.4 1640.97
    40.9    1633    45.1    1630    49.2  1627.5    53.3 1626.42    57.1 1625.96
    61.7  1624.8    65.9    1624    74.2 1623.29    78.4 1623.37    82.3 1623.84
    85.9 1624.83      91 1625.89   103.5 1630.08   107.5    1632   111.6 1634.61
     115  1636.4   119.6 1638.41   123.7 1639.21   127.7 1639.61   133.9 1640.58
   142.9 1642.36   147.9 1643.54     164 1648.68     168 1649.75   171.4 1650.25
#Mann= 5 ,-1,0
       0      .1       0   65.12     .06       0    65.9    .045       0
    82.3     .06       0  163.89      .1       0
Bank Sta=65.9,82.3
XS Rating Curve= 0 ,0
Exp/Cntr(USF)=0,0
Exp/Cntr=0.3,0.1

Type RM Length L Ch R = 1 ,5925    ,63.4,61.3,58.8
XS GIS Cut Line= 4
2157310.32079829667807.0855056572157247.37237806667783.771275941
2157204.07452287667779.7745508472157162.77503023667768.450496413
#Sta/Elev= 30
       0 1644.27     9.4 1643.11    19.4 1642.36    27.9 1641.46    36.4 1639.93
    43.6 1638.07    49.2 1636.24    57.7 1632.24      62 1630.34    67.1 1628.24
    70.3 1627.14    74.4 1625.28    78.4  1622.8    81.1 1621.74    82.4 1621.21
    90.4 1621.24    94.4 1621.68   102.5 1624.26   106.5 1625.07   110.5 1625.66
   112.5 1626.12   114.7 1626.66   118.8 1628.13   122.4 1629.19   127.1 1630.45
   131.2 1631.29   135.4 1631.66   143.7 1631.94   147.8 1631.83   153.4 1631.38
#Mann= 4 ,-1,0
       0      .1       0    81.1    .045       0    94.4      .1       0
   97.13     .06       0
Bank Sta=81.1,94.4
XS Rating Curve= 0 ,0
Exp/Cntr(USF)=0,0
Exp/Cntr=0.3,0.1

Type RM Length L Ch R = 1 ,5863    ,53.8,53.5,52.4
XS GIS Cut Line= 3
2157328.63912164667757.7925628282157279.67923924667715.826949339
2157174.76520551667726.817943348
#Sta/Elev= 30
       0 1641.24     5.9 1640.39    16.4 1638.66    31.7 1636.78    37.5 1635.66
      44  1633.8    51.8 1631.29    62.4  1628.4    64.5 1628.06      72 1627.86
    76.1 1627.64    80.1 1627.04    84.1 1625.87    88.1  1624.4    96.2 1621.94
   100.2 1620.54   104.2 1619.77   107.31619.551   116.2 1619.28   120.8 1619.48
   124.3 1619.76   125.3 1620.04   128.3 1620.92   132.4 1622.41   136.4 1623.61
   140.4 1625.19   144.4 1626.11   152.5 1627.03   156.3 1627.24     170 1627.08
#Mann= 4 ,-1,0
       0      .1       0   107.3    .045       0   120.8      .1       0
  124.48     .06       0
Bank Sta=107.3,120.8
XS Rating Curve= 0 ,0
Exp/Cntr(USF)=0,0
Exp/Cntr=0.3,0.1

Type RM Length L Ch R = 1 ,5810    ,103.9,106.5,104
XS GIS Cut Line= 3
2157356.94925773667659.5397375942157302.66040853  667655.5430125
2157159.44442599667678.857242217
#Sta/Elev= 30
       0 1634.84     4.8 1631.73    16.8  1624.5    20.8 1622.62    24.8  1621.2
    28.9 1620.35    32.9 1620.16    40.9  1620.6    52.9 1622.35      57 1622.79
    73.2 1623.97    89.4  1624.5    93.4 1624.33    97.5 1623.95   101.5 1623.31
   113.7    1620   127.7 1616.91   129.9 1616.46     134 1616.22     138 1616.24
   141.7 1616.44   143.21616.806   146.1 1617.71   150.2 1619.43   154.2 1620.39
   166.4 1622.42   174.5 1624.15   178.5 1624.76   182.6 1625.01   199.5 1624.73
#Mann= 4 ,-1,0
       0      .1       0   127.7    .045       0   143.2      .1       0
  144.44     .06       0
#XS Ineff= 2 , 0
            89.8  1627.6
Permanent Ineff=
       F       F
Bank Sta=127.7,143.2
XS Rating Curve= 0 ,0
Exp/Cntr(USF)=0,0
Exp/Cntr=0.3,0.1

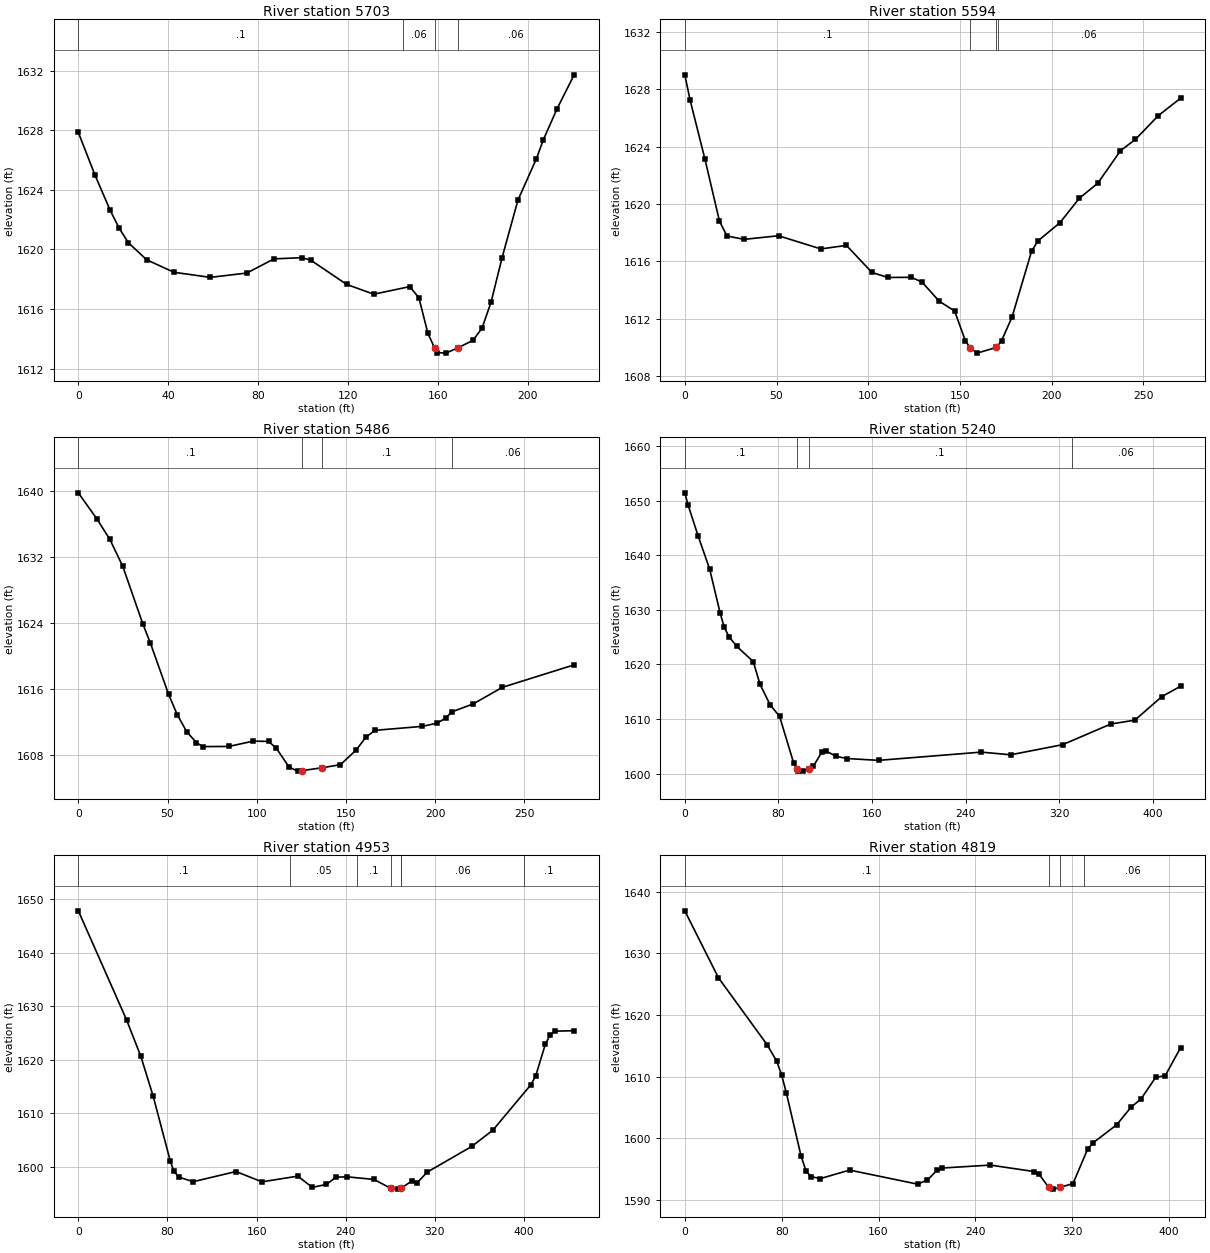
Type RM Length L Ch R = 1 ,5703    ,99.5,109.4,120.2
XS GIS Cut Line= 3
2157362.14388011667583.746042368  2157268.941786667567.755487007
2157143.30170817667579.177312265
#Sta/Elev= 30
       0 1627.85     7.4 1624.99    14.2 1622.62    18.2 1621.42    22.3 1620.45
    30.4 1619.31    42.6 1618.47    58.8 1618.13      75 1618.42    87.1 1619.37
    99.4 1619.45   103.4 1619.29   119.4 1617.66   131.5    1617   147.5 1617.51
   151.6 1616.76   155.6 1614.37   158.61613.395   159.6 1613.09   163.6 1613.05
   168.9  1613.4   175.7 1613.91   179.7 1614.73   183.7 1616.46   188.6 1619.44
   195.7 1623.32   203.8 1626.05     207 1627.36   213.1 1629.44   220.7 1631.71
#Mann= 4 ,-1,0
       0      .1       0  144.56     .06       0   158.6    .045       0
   168.9     .06       0
Bank Sta=158.6,168.9
XS Rating Curve= 0 ,0
Exp/Cntr(USF)=0,0
Exp/Cntr=0.3,0.1

Type RM Length L Ch R = 1 ,5594    ,109.1,107.8,102.6
XS GIS Cut Line= 5
2157363.05762613667554.9630427182157310.97410295667549.937439604
2157260.71807182667520.2406939342157201.78145349667454.907853458
2157132.33675592 667472.26902785
#Sta/Elev= 30
       0 1629.02     2.9 1627.25    10.9 1623.18    18.9 1618.81      23 1617.77
    32.4 1617.54    51.1 1617.79    74.2 1616.87    88.1 1617.12     102 1615.23
   110.7 1614.88   123.5 1614.89   129.4 1614.55   138.7 1613.22   147.1 1612.54
   152.9 1610.48   155.7 1609.95   159.3  1609.6   169.9    1610   172.7 1610.47
   178.4 1612.12   189.1 1616.73   192.6 1617.44   204.5  1618.7   215.1 1620.41
   225.1 1621.45   237.5 1623.72   245.7 1624.52   258.2 1626.18   270.3 1627.39
#Mann= 4 ,-1,0
       0      .1       0   155.7    .045       0   169.9      .1       0
   170.7     .06       0
Bank Sta=155.7,169.9
XS Rating Curve= 0 ,0
Exp/Cntr(USF)=0,0
Exp/Cntr=0.3,0.1

Type RM Length L Ch R = 1 ,5486    ,251,246.3,241.9
XS GIS Cut Line= 3
2157398.18570641667475.0408108362157249.34741134667375.021476548
2157152.90019613667395.263484678
#Sta/Elev= 30
       0  1639.8    10.5 1636.61    17.7 1634.15    24.9  1630.9    36.2  1623.9
    40.3 1621.65    50.6  1615.4    55.4 1612.95    60.7 1610.89    66.2 1609.54
    69.9 1609.07    84.4 1609.09    97.9 1609.73   106.6  1609.7   110.9  1608.9
   118.1 1606.59   122.9  1606.1   125.61606.165   136.71606.512   146.9 1606.88
   155.6 1608.63   161.3 1610.24   166.3 1611.04   192.8 1611.52     201 1611.91
   205.8  1612.5   209.3 1613.27   221.4 1614.25   237.7 1616.25   277.9 1618.97
#Mann= 4 ,-1,0
       0      .1       0   125.6    .045       0   136.7      .1       0
  209.32     .06       0
Bank Sta=125.6,136.7
XS Rating Curve= 0 ,0
Exp/Cntr(USF)=0,0
Exp/Cntr=0.3,0.1

Type RM Length L Ch R = 1 ,5240    ,285.4,286.8,288.9
XS GIS Cut Line= 4
2157532.73552515667263.0950786542157481.53515165667219.038943312
2157230.29610957667188.0805779382157130.27677528 667213.08541151
#Sta/Elev= 30
       0 1651.42     2.9 1649.13    11.3 1643.59    21.3 1637.42    30.1 1629.51
    33.6 1626.89    37.7 1625.11    44.3 1623.34    58.5 1620.53    64.3 1616.36
    72.9 1612.63      81  1610.5    93.1 1601.93      961600.951    97.1 1600.58
   101.2 1600.48     1061600.894   109.9 1601.39   117.3 1604.02   120.7 1604.17
   129.4 1603.18   138.6 1602.79   165.6 1602.45   253.4 1603.96   278.5 1603.47
   322.9 1605.32   364.1  1609.1   384.7 1609.81   407.7 1614.12   423.8 1616.02
#Mann= 4 ,-1,0
       0      .1       0      96    .045       0     106      .1       0
  330.68     .06       0
Bank Sta=96,106
XS Rating Curve= 0 ,0
Exp/Cntr(USF)=0,0
Exp/Cntr=0.3,0.1

Type RM Length L Ch R = 1 ,4953    ,134.7,133.5,129.2
XS GIS Cut Line= 2
 2157588.6987241667074.963473683 2157171.9514979666918.980940447
#Sta/Elev= 30
       0 1647.87    43.3 1627.48    56.1 1620.67    67.1 1613.27    82.6 1601.04
    85.7 1599.21    90.3 1598.09   103.1 1597.24   141.5 1599.14   164.8 1597.21
     197 1598.28     210 1596.17   222.7 1596.74   231.2 1598.08   241.1 1598.15
   265.4 1597.66   280.21596.017   286.7 1595.85   289.51595.987   299.5  1597.4
   303.8 1596.98   313.2 1599.04     353 1603.82   372.1 1606.88   406.3  1615.4
   410.6 1617.08   419.1 1622.91   423.4 1624.66   427.7 1625.38     445 1625.46
#Mann= 7 ,-1,0
       0      .1       0     190     .05       0     250      .1       0
   280.2    .045       0   289.5      .1       0     290     .06       0
     400      .1       0
Bank Sta=280.2,289.5
XS Rating Curve= 0 ,0
Exp/Cntr(USF)=0,0
Exp/Cntr=0.3,0.1

Type RM Length L Ch R = 1 ,4819    ,174.6,180.3,184.6
XS GIS Cut Line= 2
 2157639.8990976666882.0690432692157231.48681593666852.301384255
#Sta/Elev= 30
       0 1636.92    27.8 1626.06    67.9 1615.22    75.9 1612.53    79.9 1610.34
    83.9 1607.35      96 1597.16     100 1594.78     104  1593.8     112 1593.48
   136.1 1594.86   192.2 1592.58   200.3 1593.23   208.3 1594.83   212.3 1595.19
   252.4 1595.67   288.5 1594.62   292.5  1594.2   300.5 1592.07   304.5 1591.77
   309.61592.049   320.6 1592.67   332.6 1598.21     337 1599.25   356.7 1602.21
   368.7  1605.1   376.7 1606.37   388.8 1609.88   396.8 1610.19   409.5 1614.73
#Mann= 4 ,-1,0
       0      .1       0   300.5    .045       0   309.6      .1       0
     330     .06       0
Bank Sta=300.5,309.6
XS Rating Curve= 0 ,0
Exp/Cntr(USF)=0,0
Exp/Cntr=0.3,0.1

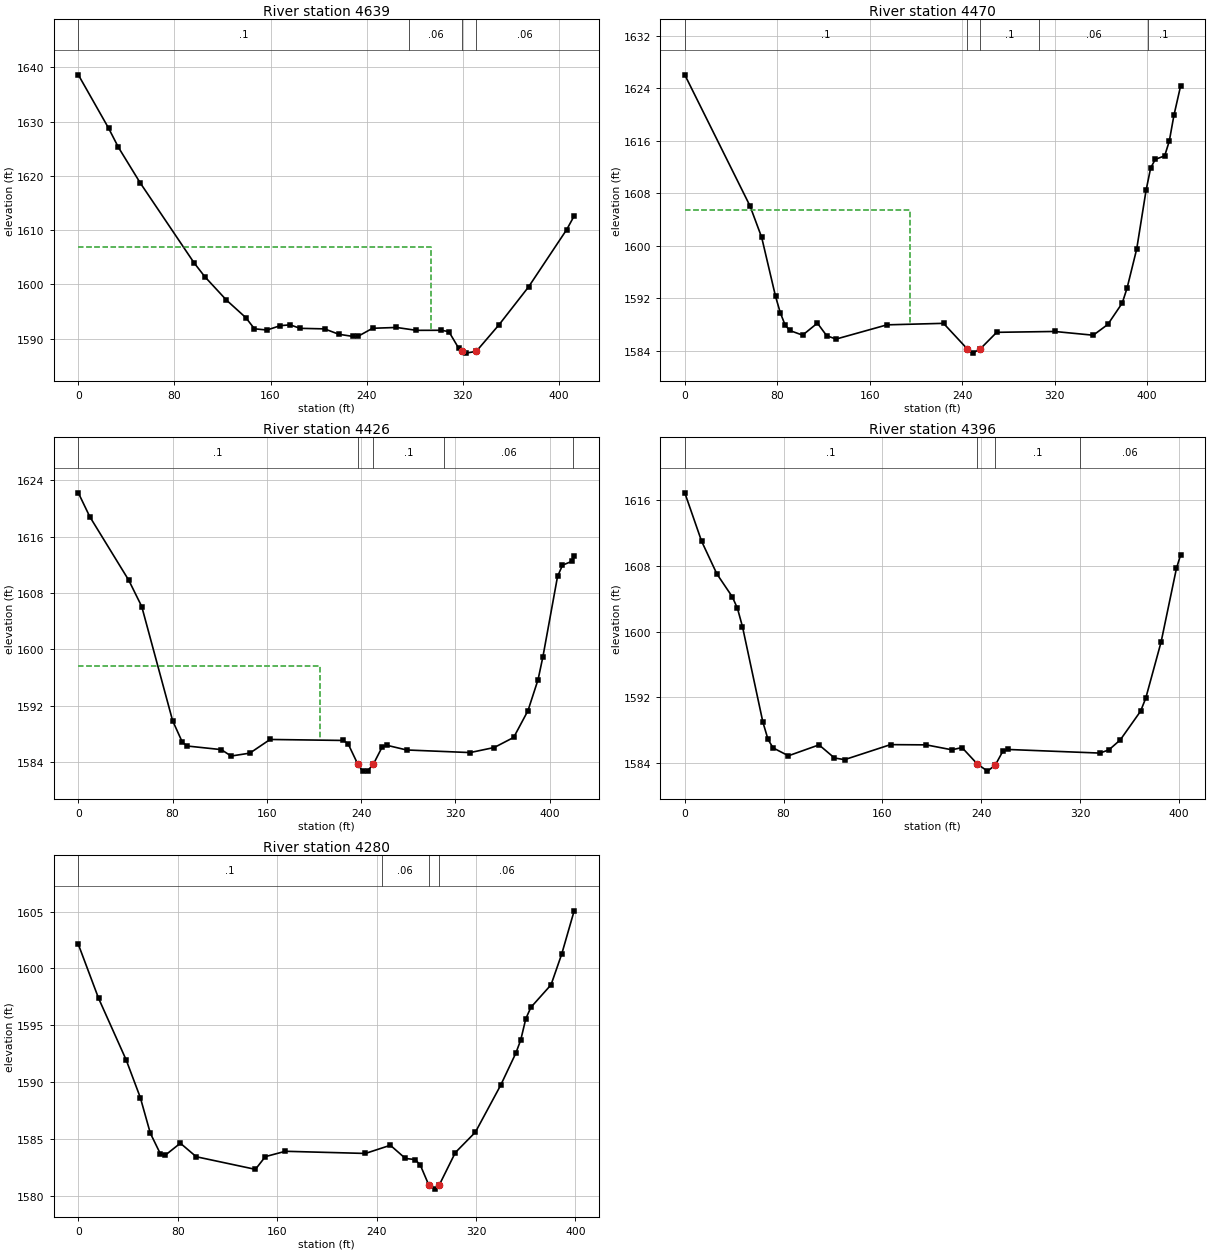
Type RM Length L Ch R = 1 ,4639    ,170.4,169,165.2
XS GIS Cut Line= 6
2157669.95318275666812.6272154432157520.28158457666736.146673516
2157489.44265637666742.7256448642157444.21222835666742.314459155
2157350.87307234666690.5050597852157290.01758737666685.982016983
#Sta/Elev= 30
       0 1638.64    25.2  1628.8    33.4 1625.26    51.4 1618.76    96.3    1604
   105.3 1601.43   123.3 1597.12   139.4 1593.89   146.6 1591.83     157 1591.61
   168.2 1592.42   176.4 1592.56   184.5 1591.92   204.9 1591.82   216.9 1590.82
   228.9 1590.42   232.9 1590.46   244.9 1591.93   264.8 1592.08   281.4 1591.55
     302 1591.56   308.4 1591.32   316.6 1588.25   319.5 1587.68   322.4 1587.35
   331.2 1587.67   350.1 1592.56   374.8 1599.57   406.5 1610.12   412.7 1612.63
#Mann= 4 ,-1,0
       0      .1       0  274.85     .06       0   319.5    .045       0
   331.2     .06       0
#XS Ineff= 2 , 0
           293.8 1606.91
Permanent Ineff=
       F       F
Bank Sta=319.5,331.2
XS Rating Curve= 0 ,0
Exp/Cntr(USF)=0,0
Exp/Cntr=0.3,0.1

Type RM Length L Ch R = 1 ,4470    ,45,44.2,43.8
XS GIS Cut Line= 5
2157704.65910188666616.6552440272157644.53210008666589.110351451
2157504.77533561666576.5761124852157328.66927814666523.305596879
2157290.43984929 666518.91861324
#Sta/Elev= 30
       0 1626.07    56.4 1606.09    66.5  1601.3    78.5  1592.3    82.6 1589.82
    86.6 1588.02    90.6 1587.12   101.9  1586.4   114.7 1588.23   122.7 1586.32
   130.8  1585.8   174.9 1587.97   223.8  1588.2   244.2 1584.33   248.9 1583.66
   255.51584.287   269.8 1586.83   319.9 1586.96   353.3 1586.39   365.9 1588.03
   378.4 1591.29   382.6 1593.59   390.9 1599.52     399 1608.46     403 1611.89
     407 1613.19   415.1 1613.72   419.1 1615.97   423.1 1619.89   428.9 1624.39
#Mann= 5 ,-1,0
       0      .1       0   244.2    .045       0   255.5      .1       0
  306.45     .06       0  400.44      .1       0
#XS Ineff= 2 , 0
          194.93 1605.44
Permanent Ineff=
       F       F
Bank Sta=244.2,255.5
XS Rating Curve= 0 ,0
Exp/Cntr(USF)=0,0
Exp/Cntr=0.3,0.1

Type RM Length L Ch R = 1 ,4426    ,30.2,30.5,30.2
XS GIS Cut Line= 2
2157717.56855755666585.4187743182157310.52030504666478.953900374
#Sta/Elev= 30
       0 1622.21     9.7 1618.83    42.8 1609.81    53.8 1606.09      80  1589.9
    88.3 1586.83    92.4 1586.31   121.3  1585.8   129.6 1584.89   145.5  1585.3
   162.7 1587.24   224.7  1587.1   228.8 1586.66   236.91583.812   241.2 1582.75
   245.4 1582.78   250.4 1583.76   257.8 1586.17   261.9 1586.41   278.5 1585.75
   332.4 1585.38   352.9  1586.1   369.4 1587.53   381.5 1591.32   390.1 1595.74
   394.2 1598.98   406.6 1610.35   410.8 1611.95     419 1612.52   420.7 1613.21
#Mann= 5 ,-1,0
       0      .1       0   236.9    .045       0   250.4      .1       0
     310     .06       0     420      .1       0
#XS Ineff= 2 , 0
          205.35 1597.59
Permanent Ineff=
       F       F
Bank Sta=236.9,250.4
XS Rating Curve= 0 ,0
Exp/Cntr(USF)=0,0
Exp/Cntr=0.3,0.1

Type RM Length L Ch R = 1 ,4396    ,118.1,115.7,112.9
XS GIS Cut Line= 2
   2157721.36349666555.8222424422157332.86630236 666454.51549153
#Sta/Elev= 30
       0 1616.91    13.6 1611.01      26 1607.02    38.4 1604.25    42.6 1602.85
    46.7  1600.6    63.2 1588.98    67.4 1586.85    71.5 1585.82    83.9 1584.86
   108.7 1586.19   121.2 1584.59   129.4 1584.39   166.6 1586.22   195.5 1586.19
   216.2 1585.59   224.5 1585.86   236.91583.854   245.1 1582.99   251.41583.724
   257.5  1585.4   261.7 1585.63   336.1 1585.19   343.4 1585.58   352.6 1586.79
   369.1  1590.3   373.3  1591.9   385.7 1598.74   398.1 1607.69   401.5 1609.35
#Mann= 4 ,-1,0
       0      .1       0   236.9    .045       0   251.4      .1       0
     320     .06       0
Bank Sta=236.9,251.4
XS Rating Curve= 0 ,0
Exp/Cntr(USF)=0,0
Exp/Cntr=0.3,0.1

Type RM Length L Ch R = 1 ,4280    ,198.6,198.1,198.1
XS GIS Cut Line= 5
2157755.71360822666426.0447011052157709.08090924666411.117437456
 2157564.7138137666394.6200418272157442.63823529666381.724734248
2157361.82764113666367.969739498
#Sta/Elev= 30
       0 1602.12    16.3 1597.37    38.5 1591.95    49.9 1588.63    57.9 1585.51
      66 1583.69      70 1583.57    82.1 1584.62    94.9 1583.43   142.5 1582.32
   150.5 1583.44   166.6 1583.91     231 1583.72   251.1 1584.44   263.2 1583.28
   271.2 1583.18   275.3 1582.67   281.9 1580.97   287.3 1580.58   290.61580.976
   303.4  1583.8   319.5 1585.59   339.8 1589.71     352 1592.53     356  1593.7
   360.1 1595.58   364.2 1596.58   380.4 1598.56     389 1601.27     399 1605.07
#Mann= 4 ,-1,0
       0      .1       0  244.27     .06       0   281.9    .045       0
   290.6     .06       0
Bank Sta=281.9,290.6
XS Rating Curve= 0 ,0
Exp/Cntr(USF)=0,0
Exp/Cntr=0.3,0.1