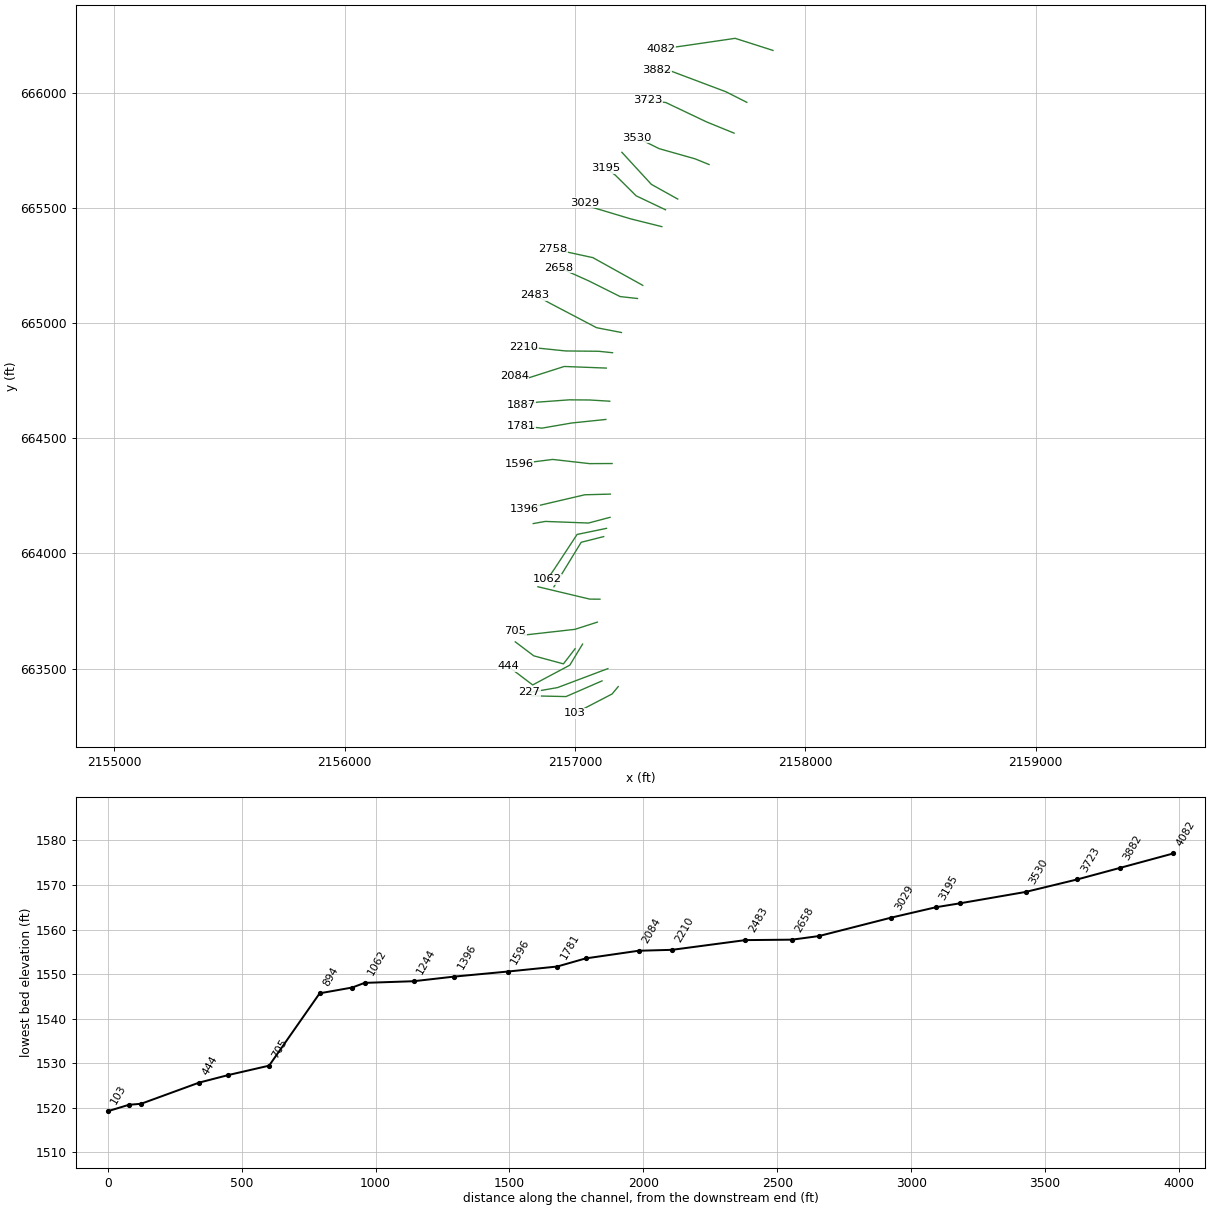
HEC-RAS study FLATWDSRN.prj: FLATWDSRN

--- FLATWDSRN.g01 (geometry) --- (continued)

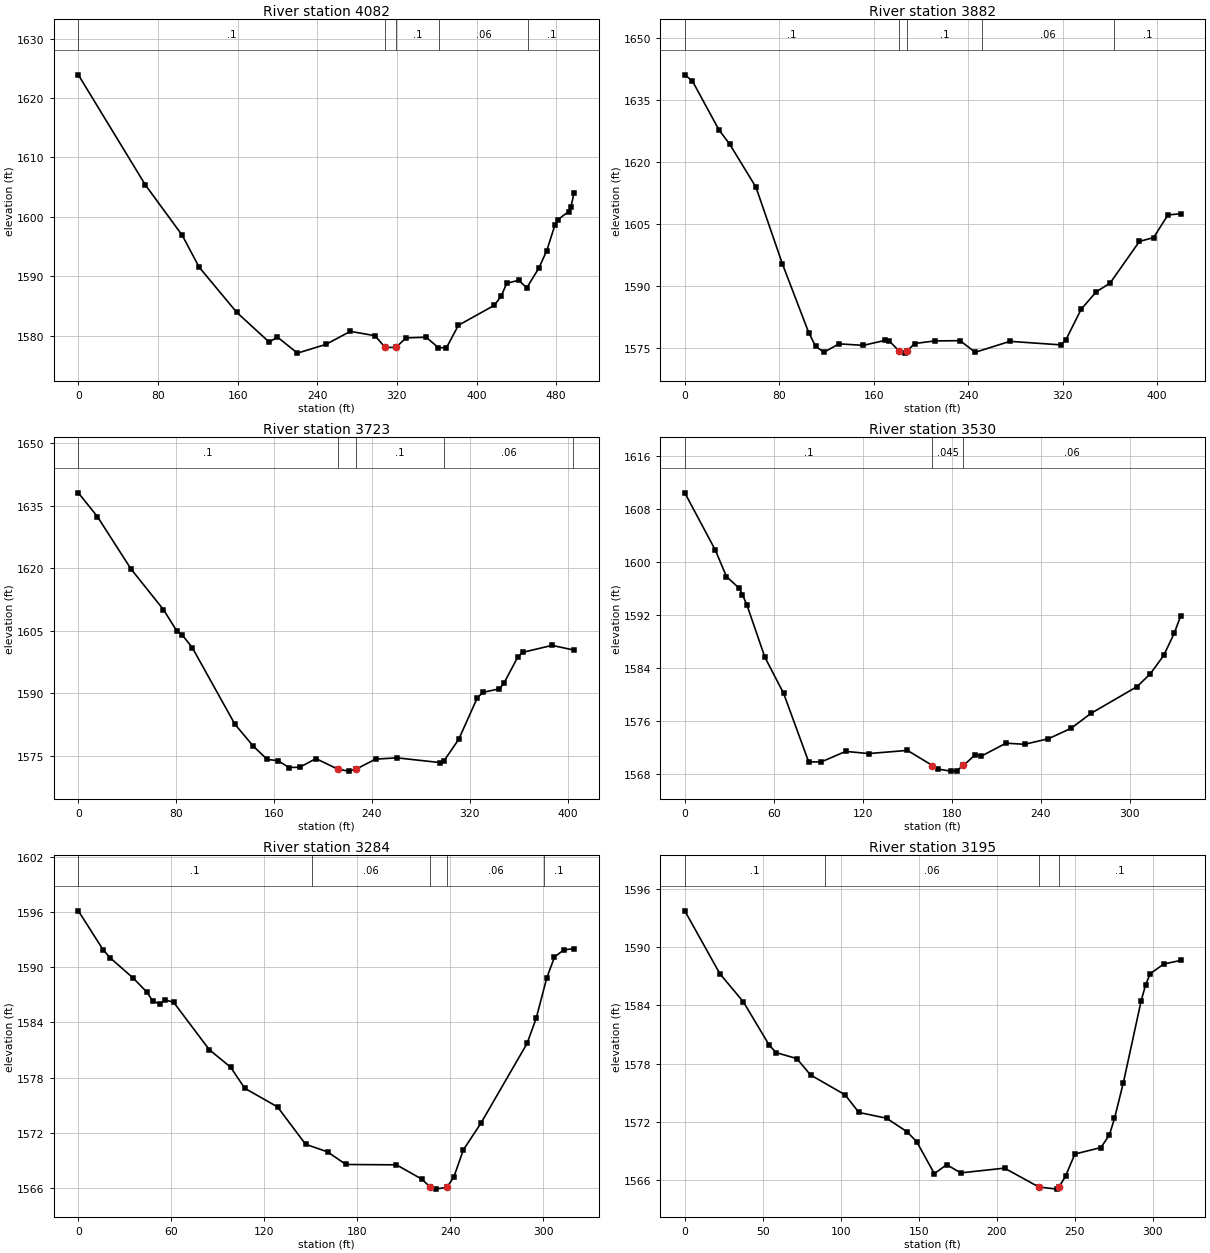
Type RM Length L Ch R = 1 ,4082    ,203.4,199.6,194.9
XS GIS Cut Line= 4
2157859.58651366666183.9966847132157695.38626383666236.437602198
2157477.88540934666204.6291768382157373.00357437666190.014494916
#Sta/Elev= 30
       0  1623.9    67.3 1605.39   104.4  1596.9   121.4 1591.54   158.9 1583.99
   191.8 1578.93   199.9 1579.81   220.1 1577.09   248.6 1578.55   273.3 1580.75
     298 1580.02   308.31578.039   319.1 1578.06   329.2 1579.65   349.4 1579.77
   361.6 1578.02   369.7 1577.96   381.8 1581.77     418 1585.14   425.1 1586.77
   430.3 1588.84   442.4 1589.34   450.5 1588.08   462.6 1591.38   470.6 1594.34
   478.7 1598.59   481.8 1599.54   492.5  1600.9   494.9 1601.73   498.1 1604.09
#Mann= 5 ,-1,0
       0      .1       0   308.3    .045       0   319.1      .1       0
  362.37     .06       0  452.19      .1       0
Bank Sta=308.3,319.1
XS Rating Curve= 0 ,0
Exp/Cntr(USF)=0,0
Exp/Cntr=0.3,0.1

Type RM Length L Ch R = 1 ,3882    ,159.6,159.6,159.5
XS GIS Cut Line= 4
2157745.99158345665958.6428152452157655.24682642666004.492797746
2157419.31045813666093.3271388422157353.40110828666100.013594623
#Sta/Elev= 30
       0  1641.1     6.5 1639.58    28.9 1627.81    37.9  1624.4    60.3 1613.93
    82.7 1595.38     105 1578.78   110.8  1575.5   117.8 1574.05   130.6 1576.08
   151.2 1575.72   169.8 1576.93   173.3 1576.75   181.4 1574.38   186.2 1573.84
   188.4 1574.38   194.7 1576.16   211.8 1576.79   233.2 1576.85     246 1574.04
   275.4 1576.69   318.7 1575.83   322.9 1577.11   335.8 1584.47   348.6 1588.67
   360.2 1590.75   385.1 1600.84   397.1 1601.75   409.2 1607.22     420 1607.54
#Mann= 5 ,-1,0
       0      .1       0   181.4    .045       0   188.4      .1       0
  251.67     .06       0  363.78      .1       0
Bank Sta=181.4,188.4
XS Rating Curve= 0 ,0
Exp/Cntr(USF)=0,0
Exp/Cntr=0.3,0.1

Type RM Length L Ch R = 1 ,3723    ,190.8,192.8,193.8
XS GIS Cut Line= 4
2157690.58952126665824.9136996172157571.18852516665873.629306024
2157394.47505094665957.6876072762157314.23758156665967.239686964
#Sta/Elev= 30
       0 1638.05    15.6 1632.34    43.1 1619.75    69.6 1610.02    80.4 1604.94
    84.7 1604.04    93.3 1600.82   127.9 1582.56   142.9 1577.29   154.4 1574.06
   163.3 1573.76   172.2 1572.12     181 1572.18   194.3 1574.26   212.3  1571.7
   220.9 1571.25   226.9  1571.7     243 1574.13   260.7 1574.43   295.5 1573.31
     299 1573.73     311 1578.88   326.3  1588.9     331 1590.16   344.3 1591.01
   347.9  1592.3   359.2 1598.59   363.2 1599.75   387.3 1601.43   405.4  1600.3
#Mann= 5 ,-1,0
       0      .1       0   212.3    .045       0   226.9      .1       0
  298.96     .06       0  404.64      .1       0
Bank Sta=212.3,226.9
XS Rating Curve= 0 ,0
Exp/Cntr(USF)=0,0
Exp/Cntr=0.3,0.1

Type RM Length L Ch R = 1 ,3530    ,254.3,246.2,238.5
XS GIS Cut Line= 4
 2157582.1854195 665688.510270232157521.38943321665713.277040898
2157365.33724909665757.4623681612157269.91197301665804.745162615
#Sta/Elev= 30
       0 1610.45    20.5 1601.84    28.1 1597.81    36.7 1596.04    38.9 1595.08
      42 1593.45      54 1585.63    66.6 1580.19    83.5 1569.85    91.9 1569.82
   108.5 1571.42     124 1571.09   150.1 1571.57     167 1569.28   170.8 1568.75
   179.2 1568.44   183.2  1568.5   187.91569.297   195.8 1570.91   199.9  1570.7
   216.6 1572.66   229.1 1572.49   245.2 1573.33   260.4  1574.9   273.8 1577.15
     305 1581.21   313.9 1583.14   322.9 1585.91     330 1589.25   334.3 1591.85
#Mann= 3 ,-1,0
       0      .1       0     167    .045       0   187.9     .06       0
Bank Sta=167,187.9
XS Rating Curve= 0 ,0
Exp/Cntr(USF)=0,0
Exp/Cntr=0.3,0.1

Type RM Length L Ch R = 1 ,3284    ,88.7,88.6,88.8
XS GIS Cut Line= 3
2157446.03608391665538.6633860422157331.69769005665602.280236762
2157203.60430144665741.549558609
#Sta/Elev= 30
       0 1596.14    15.9 1591.93    20.4 1591.05    35.6  1588.8    44.4 1587.27
    47.9 1586.35    52.5 1586.02    56.2 1586.46    61.6 1586.18    84.5 1581.05
    98.3 1579.14   107.4 1576.85   128.6 1574.82   146.7 1570.76   160.9 1569.93
   172.8 1568.56   205.4 1568.52   221.7 1566.97   227.2  1566.1   230.6 1565.88
     238 1566.08   242.4 1567.19   248.6 1570.16   259.8 1573.02   289.7 1581.72
   295.6 1584.46   302.4 1588.84   307.4 1591.11   313.3 1591.89   320.1 1592.03
#Mann= 5 ,-1,0
       0      .1       0  150.84     .06       0   227.2    .045       0
     238     .06       0  300.84      .1       0
Bank Sta=227.2,238
XS Rating Curve= 0 ,0
Exp/Cntr(USF)=0,0
Exp/Cntr=0.3,0.1

Type RM Length L Ch R = 1 ,3195    ,161.9,166.1,173.9
XS GIS Cut Line= 4
2157392.99814179665492.061268331 2157265.5667123665552.643423334
 2157175.0416531665642.4721359262157135.34989638665671.718693514
#Sta/Elev= 30
       0 1593.79    22.5 1587.28    37.5 1584.39    54.1 1579.91    58.5 1579.13
    71.8 1578.51    80.6 1576.82   102.8 1574.76   111.6 1572.94   129.4 1572.34
   142.5 1570.94   148.7 1569.91     160 1566.61   167.9 1567.54   176.9 1566.69
     205 1567.18     227 1565.23   238.6 1565.01     2401565.244   244.1 1566.35
   250.1 1568.64   266.8 1569.31   272.2  1570.6   275.5 1572.32   281.2 1576.03
   292.6 1584.49   295.5 1586.16   298.4 1587.29   307.1 1588.29   317.9 1588.66
#Mann= 4 ,-1,0
       0      .1       0      90     .06       0     227    .045       0
     240      .1       0
Bank Sta=227,240
XS Rating Curve= 0 ,0
Exp/Cntr(USF)=0,0
Exp/Cntr=0.3,0.1

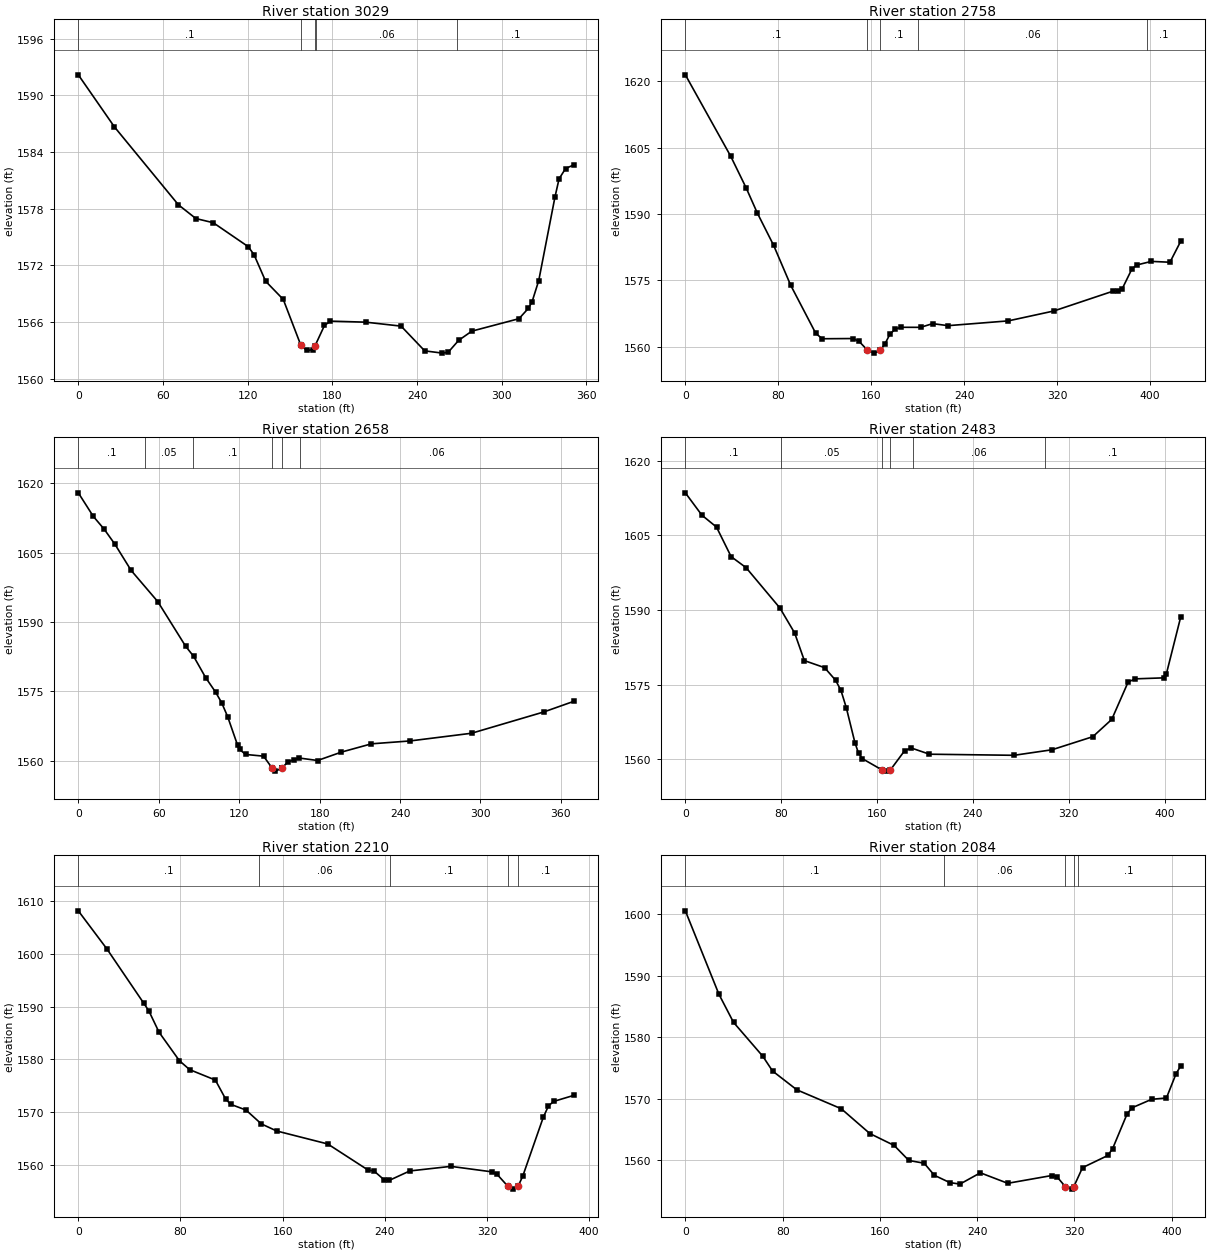
Type RM Length L Ch R = 1 ,3029    ,271,270.9,267.2
XS GIS Cut Line= 4
2157376.98216978665418.944874361 2157242.5872742665452.369511604
2157073.37504815665503.2028140792157043.43214396665522.700519137
#Sta/Elev= 30
       0 1592.18    25.6 1586.66    70.9 1578.41    83.3 1576.95    95.6 1576.51
   120.4 1573.97   124.5 1573.12   132.7 1570.31   145.2 1568.38   157.7 1563.51
   161.9 1562.97   166.1 1563.05   167.81563.496   174.4 1565.62   178.6 1566.08
   203.7 1565.97   228.7 1565.55   245.4 1562.93     258 1562.69   262.1 1562.79
   269.5 1564.05   278.8 1565.02   312.2 1566.34   318.8 1567.43   321.4  1568.1
   326.2 1570.38   337.7 1579.24   340.6 1581.16   345.2 1582.25   350.9 1582.63
#Mann= 5 ,-1,0
       0      .1       0   157.7    .045       0   167.8      .1       0
  168.49     .06       0  268.49      .1       0
Bank Sta=157.7,167.8
XS Rating Curve= 0 ,0
Exp/Cntr(USF)=0,0
Exp/Cntr=0.3,0.1

Type RM Length L Ch R = 1 ,2758    ,99.2,100.3,101.3
XS GIS Cut Line= 3
2157294.32059485665163.9347010852157077.67942753665284.290905151
2156903.16293163665322.117140714
#Sta/Elev= 30
       0 1621.46    39.1 1603.03    52.5 1595.81    61.9 1590.25      76 1582.91
    90.7 1573.88   112.3    1563   117.9 1561.79   144.3 1561.84   149.6 1561.19
   156.8  1559.2   162.6 1558.54   167.91559.183   171.8 1560.62   176.3  1562.9
   180.9 1563.99   185.5 1564.38   202.5 1564.37   212.9 1565.21   226.1 1564.75
     278 1565.83   317.1 1568.06   368.1 1572.54   372.2 1572.62   376.2 1573.15
   384.4 1577.54   388.5 1578.46   401.2 1579.28   417.2 1579.09   426.4  1583.8
#Mann= 5 ,-1,0
       0      .1       0   156.8    .045       0   167.9      .1       0
     200     .06       0  397.83      .1       0
Bank Sta=156.8,167.9
XS Rating Curve= 0 ,0
Exp/Cntr(USF)=0,0
Exp/Cntr=0.3,0.1

Type RM Length L Ch R = 1 ,2658    ,173.9,174.4,173.9
XS GIS Cut Line= 4
2157271.31554263665106.8456284042157196.11010884665115.201787714
2157061.01886664 665182.747408812156930.80205072665241.240523986
#Sta/Elev= 30
       0 1617.96    11.2 1612.86    19.3 1610.09    27.3 1606.84    39.4 1601.17
    59.3 1594.41    80.1 1584.74      86 1582.59      95 1577.97   102.4 1574.83
   106.9 1572.56   111.4 1569.53   118.8 1563.36   120.3 1562.42   124.8 1561.34
   138.2 1560.97   144.71558.343   147.1 1557.73   151.6 1558.34   151.6 1558.35
   156.1 1559.62   160.6 1560.22     165 1560.56   178.5 1560.03   196.3 1561.85
   218.7 1563.64   247.4 1564.26   293.4 1565.93   347.2 1570.53   369.5 1572.82
#Mann= 6 ,-1,0
       0      .1       0      50     .05       0   85.67      .1       0
   144.7    .045       0   151.6      .1       0  165.67     .06       0
Bank Sta=144.7,151.6
XS Rating Curve= 0 ,0
Exp/Cntr(USF)=0,0
Exp/Cntr=0.3,0.1

Type RM Length L Ch R = 1 ,2483    ,268.1,273.3,275.5
XS GIS Cut Line= 4
2157201.68088171664959.2201472462157093.74715728664980.110545523
2156894.59202704665084.5625369082156825.65371272665122.165253807
#Sta/Elev= 30
       0 1613.55    13.8 1609.06      26 1606.67    38.2 1600.73    50.7 1598.51
    78.9 1590.41    91.2 1585.39    99.3 1579.84   116.2 1578.42   125.3 1575.91
   129.8 1573.88   134.3 1570.38   141.5 1563.35   144.5 1561.24   147.8 1560.12
   163.9  1557.9   168.2 1557.63   171.1 1557.87     183 1561.74   188.5 1562.28
   203.7 1561.03   274.3 1560.81   305.9 1561.92     340 1564.55   355.8 1568.02
   369.5 1575.54   375.4 1576.17     399 1576.37   401.4 1577.18   413.3 1588.56
#Mann= 6 ,-1,0
       0      .1       0      80     .05       0   163.9    .045       0
   171.1     .05       0  189.94     .06       0  299.94      .1       0
Bank Sta=163.9,171.1
XS Rating Curve= 0 ,0
Exp/Cntr(USF)=0,0
Exp/Cntr=0.3,0.1

Type RM Length L Ch R = 1 ,2210    ,121.9,125.6,128.9
XS GIS Cut Line= 4
2157163.10315691664871.472408281 2157101.8246553664877.739527764
2156959.76994702664879.1322209832156776.63078879664897.933579432
#Sta/Elev= 30
       0 1608.14    22.5 1600.89    51.2 1590.66    55.2 1589.21    63.2 1585.16
    79.2 1579.75    87.2 1578.07   107.3  1576.1   115.3 1572.53   119.3 1571.51
   131.3 1570.42   143.3  1567.8   155.3 1566.46   195.3    1564     227 1559.04
   231.4 1558.91   239.4 1557.22   243.5 1557.11   259.5 1558.89   291.7 1559.76
   323.9 1558.72   327.9 1558.24   336.4 1555.97     340 1555.45   344.3 1555.98
     348 1557.92   364.1 1569.08   368.1 1571.19   372.1 1572.05   387.8 1573.19
#Mann= 5 ,-1,0
       0      .1       0   141.6     .06       0  243.66      .1       0
   336.4    .045       0   344.3      .1       0
Bank Sta=336.4,344.3
XS Rating Curve= 0 ,0
Exp/Cntr(USF)=0,0
Exp/Cntr=0.3,0.1

Type RM Length L Ch R = 1 ,2084    ,199.2,197.8,193.9
XS GIS Cut Line= 4
2157135.79089546664804.7778774852156953.19334015664811.741343578
2156800.77080457664762.9970809312156736.55217283664769.186828569
#Sta/Elev= 30
       0 1600.59    27.6    1587    39.6 1582.42    63.7 1576.89    71.7 1574.49
    91.7 1571.42   128.2 1568.34   151.7  1564.3   171.7 1562.36   183.8 1559.91
   196.4 1559.46   204.8 1557.49   217.4 1556.31   225.8 1556.06   242.6  1557.9
   265.1 1556.19   301.4 1557.46   305.6 1557.25   312.41555.661   318.2 1555.24
   319.4 1555.63   326.6 1558.74   347.4 1560.72   351.4 1561.86   363.4 1567.56
   367.5 1568.51   383.5 1569.88   395.6 1570.09   403.6 1574.08   407.3 1575.29
#Mann= 5 ,-1,0
       0      .1       0  212.73     .06       0   312.4    .045       0
   319.4     .06       0  322.73      .1       0
Bank Sta=312.4,319.4
XS Rating Curve= 0 ,0
Exp/Cntr(USF)=0,0
Exp/Cntr=0.3,0.1

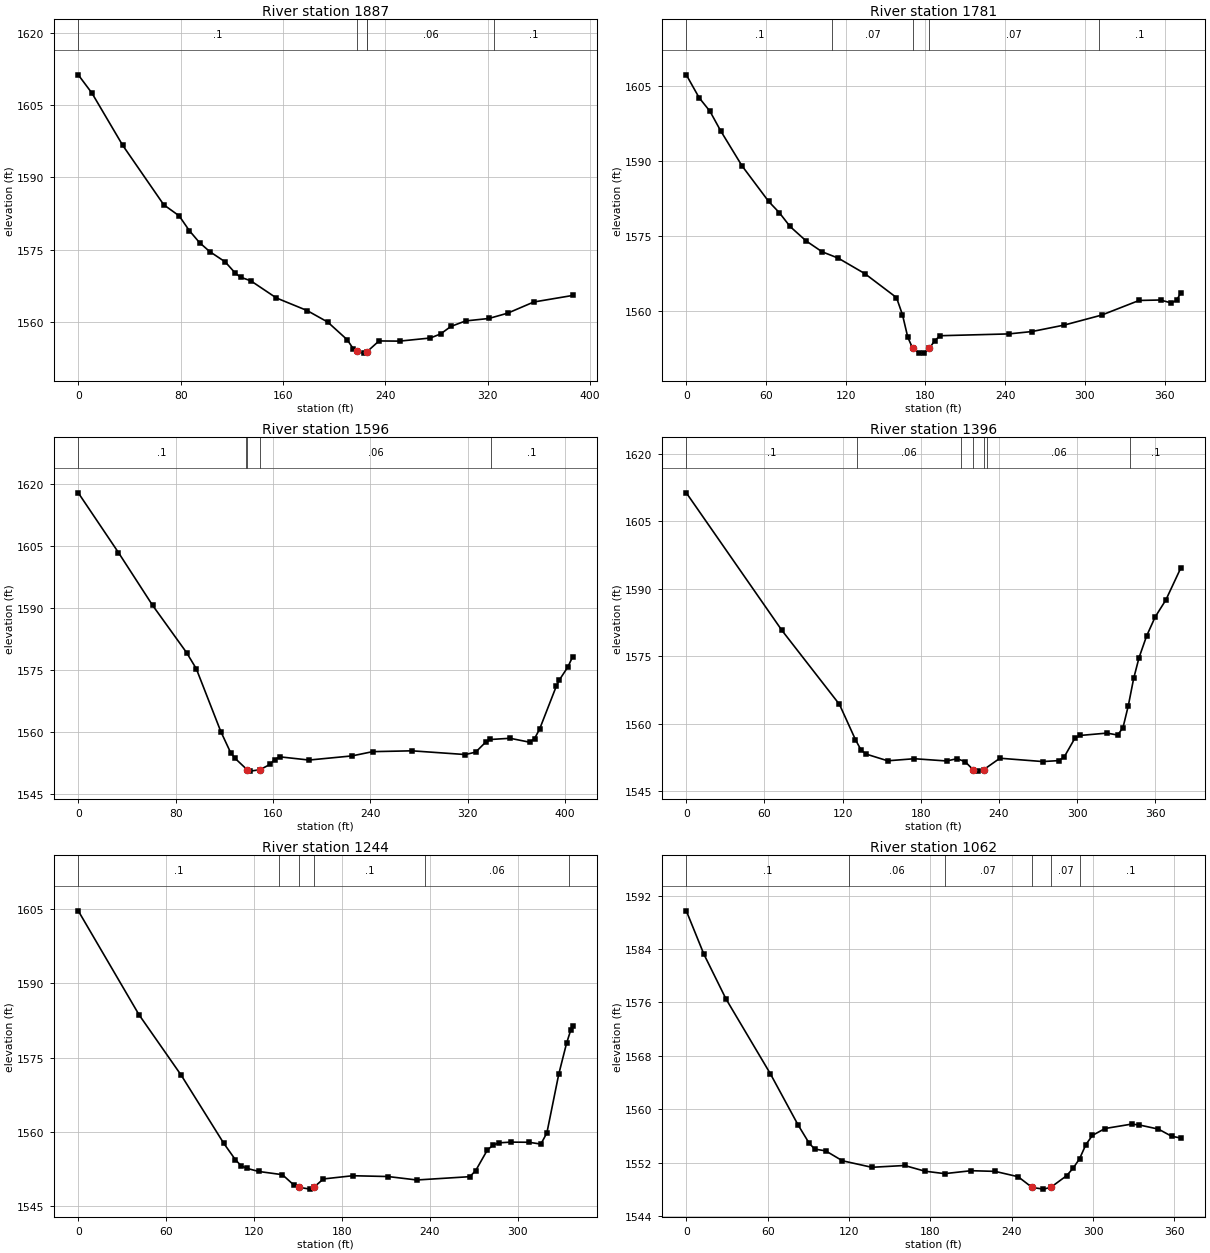
Type RM Length L Ch R = 1 ,1887    ,105.4,106,106.7
XS GIS Cut Line= 5
2157150.83236885664660.9258097632157063.87459867664666.203628607
2156975.06582511664666.8694655912156836.57022172 664656.81112568
2156766.32495786664643.599280626
#Sta/Elev= 30
       0 1611.28    10.7 1607.48    34.7 1596.66    66.8 1584.31    78.8 1582.02
    86.8 1578.94    94.8 1576.44   102.8 1574.58   114.8 1572.46   122.8 1570.09
   126.8 1569.28   134.8 1568.53   154.8 1564.97   178.8 1562.36   194.9 1559.97
   210.1 1556.31   214.9 1554.42   217.6 1553.87   222.9 1553.52   225.81553.855
     235 1556.05     251 1556.01   275.1 1556.66   283.1  1557.5   291.1 1559.05
   302.6  1560.2   320.8 1560.71   335.5 1561.81   355.9 1564.13   386.3 1565.49
#Mann= 5 ,-1,0
       0      .1       0   217.6    .045       0   225.8      .1       0
  225.93     .06       0  324.79      .1       0
Bank Sta=217.6,225.8
XS Rating Curve= 0 ,0
Exp/Cntr(USF)=0,0
Exp/Cntr=0.3,0.1

Type RM Length L Ch R = 1 ,1781    ,187.9,185.2,182.6
XS GIS Cut Line= 4
2157133.86301772664581.7224631092156985.13713699664566.248094015
 2156856.1840612664543.8962275452156765.05722098664554.212473608
#Sta/Elev= 30
       0 1607.17     9.7 1602.59    17.8 1599.91    25.8 1596.04    41.9 1589.04
      62 1581.93    70.1 1579.67    78.1 1576.94    90.2 1574.06   102.2  1571.9
   114.3 1570.64   134.4 1567.54   158.2 1562.77   162.7 1559.35   166.7 1554.86
   170.41552.653   175.5  1551.7   178.9 1551.72     183 1552.66     187  1554.2
   191.1 1555.17   242.7 1555.53   260.1    1556   284.4 1557.29   312.6 1559.28
   340.8  1562.2   356.9 1562.29     365  1561.7     369 1562.22   372.1 1563.67
#Mann= 5 ,-1,0
       0      .1       0     110     .07       0   170.4    .045       0
     183     .07       0   310.4      .1       0
Bank Sta=170.4,183
XS Rating Curve= 0 ,0
Exp/Cntr(USF)=0,0
Exp/Cntr=0.3,0.1

Type RM Length L Ch R = 1 ,1596    ,195.9,199.4,201.1
XS GIS Cut Line= 4
2157161.15616919664390.3797392172157063.19428528664389.955202343
2156903.35615184664408.104153749 2156757.1031984664389.636799686
#Sta/Elev= 30
       0 1617.85      33 1603.42      61 1590.68      89 1579.22      97 1575.31
   117.1 1560.15   125.2 1555.03   128.9 1553.64   138.6 1550.95   141.3 1550.57
   149.3 1550.91   157.4 1552.18   161.4 1553.35   165.4 1554.03   189.6 1553.25
   224.9 1554.25   241.9 1555.28   274.1 1555.48     318 1554.58   326.5 1555.16
   334.6 1557.54   338.6 1558.22   354.8 1558.51   370.9 1557.56   374.9 1558.45
     379  1560.7   392.9  1571.2   395.1 1572.54   402.2 1575.72   406.2 1578.22
#Mann= 5 ,-1,0
       0      .1       0  137.96     .06       0   138.6    .045       0
   149.3     .06       0  338.83      .1       0
Bank Sta=138.6,149.3
XS Rating Curve= 0 ,0
Exp/Cntr(USF)=0,0
Exp/Cntr=0.3,0.1

Type RM Length L Ch R = 1 ,1396    ,150.7,152,143.2
XS GIS Cut Line= 3
2157153.56939052664257.5738836892157042.76526614664254.708259783
 2156781.0382827664193.574949781
#Sta/Elev= 30
       0 1611.36    73.4 1580.76   117.6 1564.28   129.9 1556.43   134.2 1554.12
   138.1 1553.23   154.6 1551.74   175.1  1552.2   199.8  1551.7     208 1552.21
   214.2 1551.51   220.3 1549.74   224.2 1549.44   228.5  1549.8   240.8 1552.31
   273.7 1551.57     286 1551.78   290.1 1552.56   298.3 1556.73   302.5 1557.38
     323  1557.9   331.2 1557.47   335.3 1559.13   339.4 1564.03   343.5 1570.08
   347.6 1574.67   353.4 1579.49     360 1583.74   368.2 1587.52   379.6 1594.59
#Mann= 7 ,-1,0
       0      .1       0  130.84     .06       0  210.84      .1       0
   220.3    .045       0   228.5      .1       0  230.84     .06       0
  340.84      .1       0
Bank Sta=220.3,228.5
XS Rating Curve= 0 ,0
Exp/Cntr(USF)=0,0
Exp/Cntr=0.3,0.1

Type RM Length L Ch R = 1 ,1244    ,173.1,182.7,196.4
XS GIS Cut Line= 4
2157152.27892268664156.7560054872157058.65898966664131.997014937
2156870.64540516664138.960481029 2156818.8062687664129.675859572
#Sta/Elev= 30
       0  1604.7    41.5 1583.67    70.4  1571.4    99.3 1557.69   107.3 1554.35
   111.3  1553.1   115.3 1552.59   123.3 1551.97   139.4 1551.32   147.4 1549.18
   150.61548.772   158.3  1548.4     1611548.808   167.4 1550.46   187.4 1551.11
   211.4 1550.95   231.2 1550.25   267.4 1550.92   271.4 1552.16   279.4 1556.34
   283.5 1557.34   287.5 1557.77   295.5 1557.91   307.8 1557.88   315.9 1557.51
     320 1559.78   328.1 1571.65   333.4 1577.87   336.3 1580.59   337.6 1581.36
#Mann= 6 ,-1,0
       0      .1       0  136.84     .06       0   150.6    .045       0
     161      .1       0  236.84     .06       0  334.98      .1       0
Bank Sta=150.6,161
XS Rating Curve= 0 ,0
Exp/Cntr(USF)=0,0
Exp/Cntr=0.3,0.1

Type RM Length L Ch R = 1 ,1062    ,46,46,43.2
XS GIS Cut Line= 4
2157136.88583109664108.8577032422157009.14100856664082.479033835
2156911.15029969663933.4004860642156879.16918897663887.713185032
#Sta/Elev= 30
       0 1589.72      13 1583.21    29.3 1576.51      62 1565.31    82.4 1557.66
    90.6 1554.91    94.7 1554.03   102.8 1553.76   115.1 1552.28   136.8  1551.3
     161 1551.57   175.9 1550.72   190.5 1550.35   210.1 1550.79   227.7 1550.69
   244.7 1549.89     2551548.285   263.3 1548.03   268.71548.284   280.4 1550.03
   285.2 1551.15     290 1552.57   294.7 1554.71   299.5 1556.08   308.8 1557.11
   328.4 1557.77   334.1 1557.64   348.2 1557.02   357.9 1555.95   364.6 1555.69
#Mann= 6 ,-1,0
       0      .1       0     120     .06       0  190.44     .07       0
     255    .045       0   268.7     .07       0  290.44      .1       0
Bank Sta=255,268.7
XS Rating Curve= 0 ,0
Exp/Cntr(USF)=0,0
Exp/Cntr=0.3,0.1

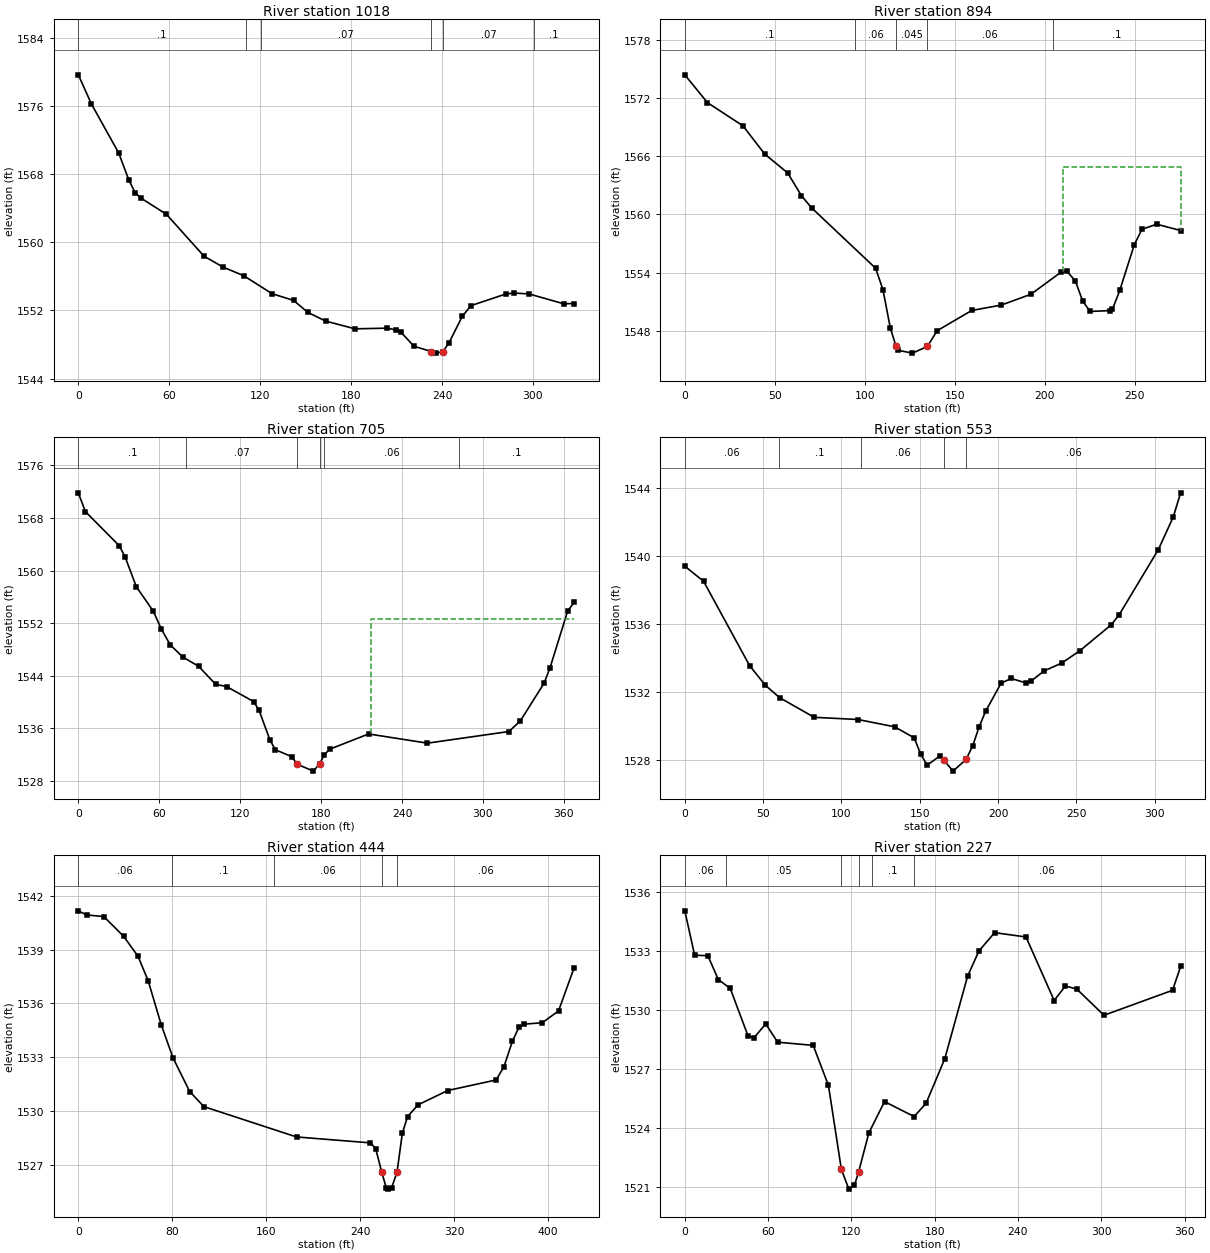
Type RM Length L Ch R = 1 ,1018    ,134.4,121.8,109.5
XS GIS Cut Line= 3
2157124.54796187664073.0778670232157026.93653302664048.435421828
 2156908.6121163663855.224437632
#Sta/Elev= 30
       0 1579.65     8.6 1576.24    26.6 1570.49    33.4 1567.28    37.5 1565.81
    41.6 1565.15    58.1 1563.29    82.9 1558.37    95.7 1557.07   109.2 1556.07
   127.9 1553.96     142 1553.18   151.4 1551.78   163.2 1550.75   182.6 1549.84
     204 1549.92   209.8  1549.7   212.7 1549.49   221.4 1547.81     233 1547.17
   235.8 1546.99   240.5 1547.15   244.7 1548.23   253.4 1551.32   259.2 1552.57
   282.1 1553.93   287.4 1554.04   297.4 1553.94   320.3 1552.78   327.2 1552.81
#Mann= 6 ,-1,0
       0      .1       0  110.67     .06       0  120.67     .07       0
     233    .045       0   240.5     .07       0  300.67      .1       0
Bank Sta=233,240.5
XS Rating Curve= 0 ,0
Exp/Cntr(USF)=0,0
Exp/Cntr=0.3,0.1

Type RM Length L Ch R = 1 ,894     ,186.4,188.8,191.9
XS GIS Cut Line= 3
2157108.45660505 663801.37748641 2157064.0499169663801.661952322
2156839.22580132  663855.3127999
#Sta/Elev= 30
       0  1574.4    12.6 1571.53    32.3 1569.14    44.4 1566.23    57.2 1564.27
    64.8 1561.93    70.5 1560.67     106 1554.45   110.1 1552.24   114.2 1548.28
   117.4 1546.38   118.3 1545.99   126.5 1545.69   134.8 1546.38   140.2    1548
   159.4 1550.09   175.9 1550.65   192.3 1551.76   208.8 1554.01   212.3 1554.14
     217 1553.14   221.1 1551.05   225.2 1549.99   236.5 1550.08   237.6  1550.2
   241.7 1552.17   249.7 1556.84     254 1558.46   262.2 1558.99   275.5 1558.34
#Mann= 5 ,-1,0
       0      .1       0   94.41     .06       0   117.4    .045       0
   134.8     .06       0  204.41      .1       0
#XS Ineff= 2 , 0
                          210.08         1564.94
Permanent Ineff=
       F       F
Bank Sta=117.4,134.8
XS Rating Curve= 0 ,0
Exp/Cntr(USF)=0,0
Exp/Cntr=0.3,0.1

Type RM Length L Ch R = 1 ,705     ,152.9,151.9,147.7
XS GIS Cut Line= 4
2157097.09353098663701.7476115342156999.69957128663670.437804734
2156781.76692646663645.8976899252156739.76455799663664.712288169
#Sta/Elev= 30
       0 1571.83     5.2 1568.98    30.4 1563.76    34.6 1562.11      43 1557.53
    55.6  1553.8    61.6 1551.05    68.2 1548.67    77.5 1546.82    89.2 1545.41
   101.8 1542.67   109.9 1542.33     130 1540.04     134 1538.71   142.1 1534.17
   146.1  1532.7   158.2 1531.66   162.2  1530.5   174.3 1529.45     179 1530.61
   182.3 1531.94   186.4 1532.79   215.2 1535.11   258.8 1533.71   319.2 1535.48
   327.7 1537.09   345.3 1542.85   349.7 1545.18   362.8 1553.85   367.6 1555.14
#Mann= 6 ,-1,0
       0      .1       0      80     .07       0   162.2    .045       0
     179     .07       0   182.3     .06       0   282.3      .1       0
#XS Ineff= 2 , 0
                          217.24         1552.56
Permanent Ineff=
       F       F
Bank Sta=162.2,179
XS Rating Curve= 0 ,0
Exp/Cntr(USF)=0,0
Exp/Cntr=0.3,0.1

Type RM Length L Ch R = 1 ,553     ,101.6,109.7,118.2
XS GIS Cut Line= 4
2157000.26304393663585.9607281562156949.79012154663520.514876535
2156821.06995137663555.3665248612156740.81980554663616.020617023
#Sta/Elev= 30
       0 1539.42      12 1538.53    41.4 1533.56    51.5  1532.4    60.5 1531.68
    82.6 1530.52   110.6 1530.39     134 1529.96   146.5 1529.31   150.6 1528.35
   154.8  1527.7   163.1 1528.26   165.31528.008   171.3 1527.35   179.6 1528.04
   183.8 1528.83   187.9 1529.95   192.1 1530.88   201.9 1532.52   208.4 1532.81
   217.9 1532.54   220.8 1532.63   229.4 1533.25   240.8 1533.72   252.4 1534.45
   272.3 1535.97   277.3 1536.55   302.4  1540.4   311.9 1542.32   316.6 1543.74
#Mann= 5 ,-1,0
       0     .06       0      60      .1       0  112.65     .06       0
   165.3    .045       0   179.6     .06       0
Bank Sta=165.3,179.6
XS Rating Curve= 0 ,0
Exp/Cntr(USF)=0,0
Exp/Cntr=0.3,0.1

Type RM Length L Ch R = 1 ,444     ,219.6,216.6,216
XS GIS Cut Line= 4
2157032.90923931663606.241200555 2156977.3643236663514.838174703
2156816.35437806663429.0599504432156710.18624804663509.213373112
#Sta/Elev= 30
       0 1541.16     7.1 1540.93    21.7 1540.84    38.7 1539.73    50.8 1538.63
    59.5 1537.26    70.7 1534.79    80.8 1532.94    94.9 1531.08     107 1530.24
   185.9 1528.55   248.8 1528.22   253.3  1527.9  258.47 1526.59   262.4 1525.69
   263.6 1525.64   266.9 1525.72   271.5 1526.58     276 1528.75   280.5 1529.69
   289.4 1530.34   314.7 1531.14     356 1531.73   362.6 1532.47   369.8 1533.89
   375.3 1534.66   379.8 1534.84   395.3 1534.92   409.1 1535.58   422.4 1537.99
#Mann= 5 ,-1,0
       0     .06       0      80      .1       0  166.96     .06       0
  258.47    .045       0   271.5     .06       0
Bank Sta=258.47,271.5
XS Rating Curve= 0 ,0
Exp/Cntr(USF)=0,0
Exp/Cntr=0.3,0.1

Type RM Length L Ch R = 1 ,227     ,44.7,45.2,45.6
XS GIS Cut Line= 4
2157142.84570698663499.7784890322157110.14387752663487.695482669
2156924.06046102663417.4681771982156802.44628376663396.419569596
#Sta/Elev= 30
       0 1535.04     7.1 1532.78    16.6 1532.76    24.2 1531.54    32.7  1531.1
    45.5 1528.69    49.8 1528.58    58.3 1529.29    66.9 1528.36    92.5  1528.2
   103.5 1526.16   112.8 1521.89   118.2 1520.89   122.2 1521.08   125.21521.758
   132.6 1523.75   143.9 1525.34   165.2 1524.58   173.8 1525.25   187.3 1527.52
   203.7 1531.71   211.9    1533   223.2 1533.93   245.8 1533.71   266.1 1530.48
   274.2 1531.22   282.4 1531.06     302 1529.73   351.4    1531   357.2 1532.21
#Mann= 6 ,-1,0
       0     .06       0      30     .05       0   112.8    .045       0
   125.2     .05       0  134.86      .1       0  164.86     .06       0
Bank Sta=112.8,125.2
XS Rating Curve= 0 ,0
Exp/Cntr(USF)=0,0
Exp/Cntr=0.3,0.1

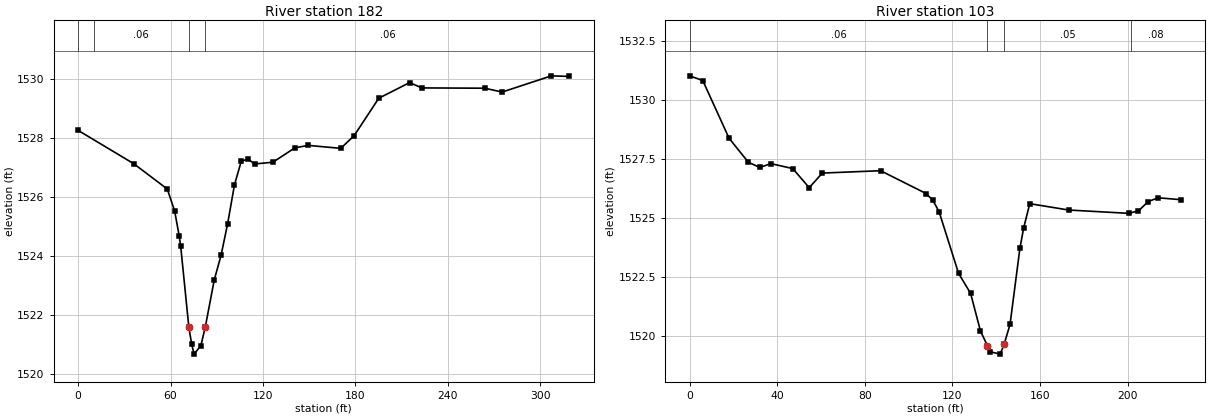
Type RM Length L Ch R = 1 ,182     ,79.4,79.1,79.4
XS GIS Cut Line= 3
2157117.25079101 663446.576911742156960.92312863663378.570629871
 2156812.4984999663381.697758918
#Sta/Elev= 30
       0 1528.26    36.1 1527.13    57.9 1526.27    62.7 1525.52    65.7 1524.66
    66.6 1524.33    71.91521.579    73.7 1521.02    75.3 1520.67    79.7 1520.96
    82.61521.598    88.4 1523.19    92.8 1524.02    97.1  1525.1   101.5 1526.41
   105.9 1527.21   110.2 1527.29   114.6 1527.12   126.5 1527.18   140.8 1527.67
   149.5 1527.75   170.5 1527.65   179.2 1528.08   195.2 1529.35   215.2 1529.88
   223.2  1529.7   263.9 1529.69   275.3 1529.56   307.3 1530.11   318.9 1530.09
#Mann= 4 ,-1,0
       0     .05       0      10     .06       0    71.9    .045       0
    82.6     .06       0
Bank Sta=71.9,82.6
XS Rating Curve= 0 ,0
Exp/Cntr(USF)=0,0
Exp/Cntr=0.3,0.1

Type RM Length L Ch R = 1 ,103     ,,,
XS GIS Cut Line= 3
2157187.63352371663421.7969132962157161.17235257663389.834603934
2156998.92359261663305.576664217
#Sta/Elev= 30
       0 1531.04       6 1530.84      18 1528.39    26.8 1527.37      32 1527.15
    37.2 1527.31    47.1  1527.1    54.6 1526.29    60.6 1526.91    87.2 1527.01
     108 1526.04     111 1525.76   113.9 1525.27   122.8 1522.65   128.3  1521.8
   132.8  1520.2     1361519.574   137.3 1519.32   141.8 1519.22   143.6 1519.64
   146.3 1520.48   150.8 1523.71   152.5 1524.57   155.3 1525.61   173.1 1525.34
   200.4  1525.2   204.9  1525.3   209.4  1525.7   213.9 1525.86   224.3 1525.78
#Mann= 4 ,-1,0
       0     .06       0     136    .045       0   143.6     .05       0
  201.49     .08       0
Bank Sta=136,143.6
XS Rating Curve= 0 ,0
Exp/Cntr(USF)=0,0
Exp/Cntr=0.3,0.1
LCMann Table=0

Chan Stop Cuts=-1
Use User Specified Reach Order=0
Composite Channel Slope=5